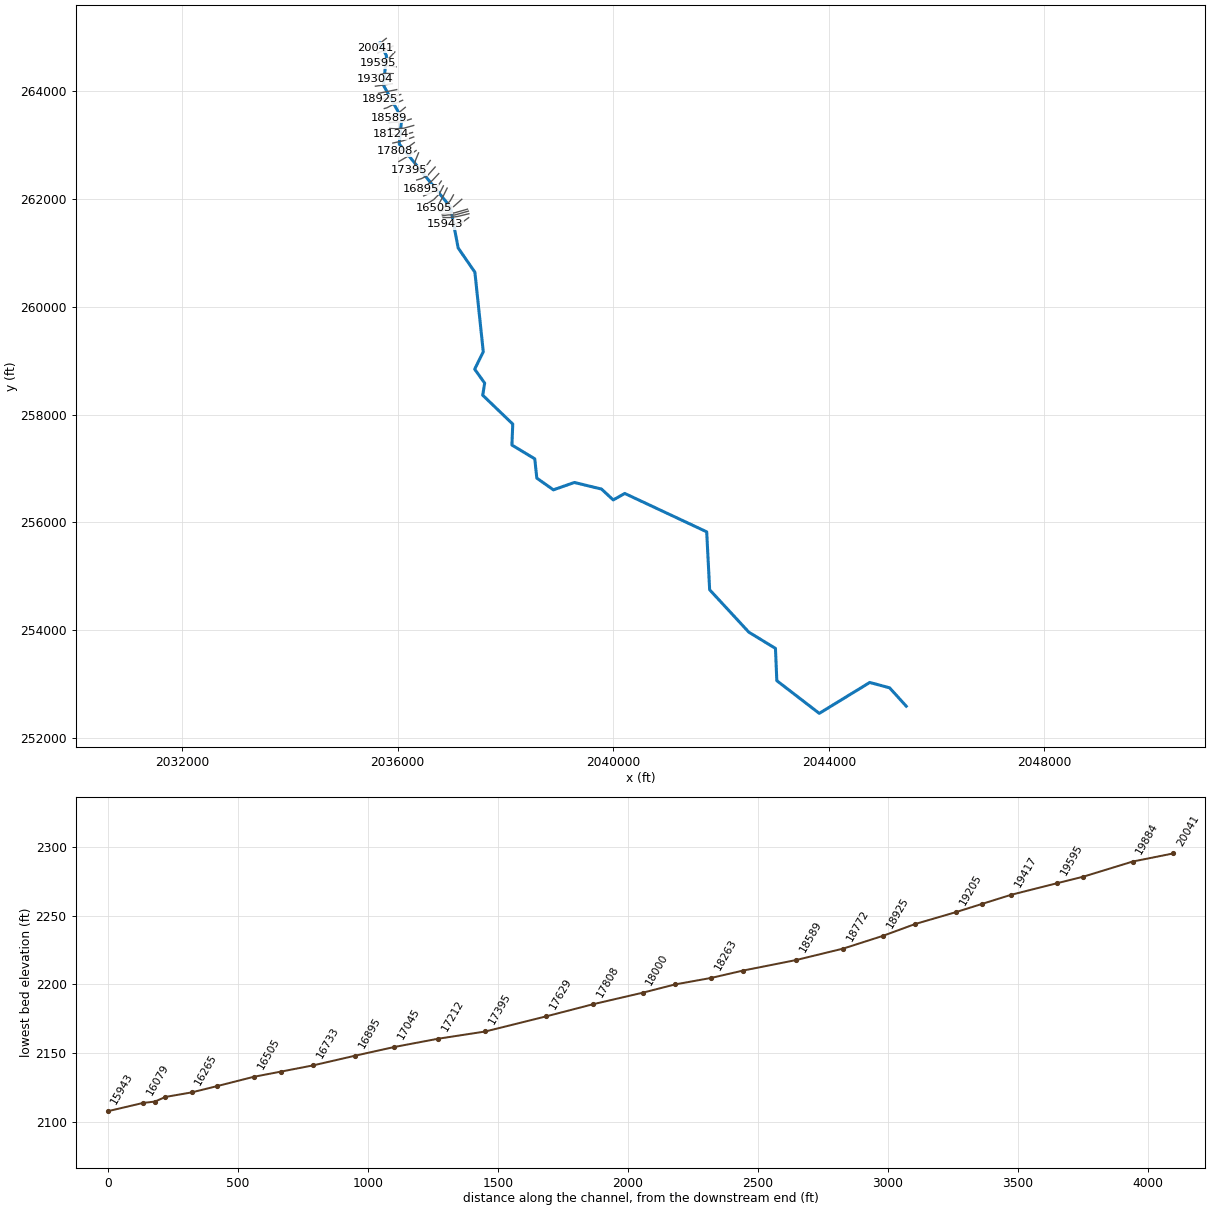
--- HNGRDCK_2.prj (project) ---

Proj Title=HNGRDCK_2
Current Plan=p01
Default Exp/Contr=0,0
English Units
Geom File=g01
Flow File=f01
Plan File=p01
BEGIN DESCRIPTION:
Stream Name: Hungard Creek 2
Flood Zone: Approximate
Summers County, West Virginia
HEC-RAS Version: 5.0.7
Hydrology Method:
Regression.
Model Notes:
END DESCRIPTION:
DSS File=dss
DSS Export Rating Curves= 0
DSS Export Rating Curve Sorted= 0
DSS Export Volume Flow Curves= 0
DXF OffsetX= 0
DXF OffsetY= 0
DXF ScaleX= 0
DXF ScaleY= 0

--- HNGRDCK_2.p01 (plan) ---

Plan Title=Floodplain
Program Version=5.07
Short Identifier=Floodplain
Geom File=g01
Flow File=f01
Subcritical Flow
K Sum by GR= 0
Std Step Tol= 0.01
Critical Tol= 0.01
Num of Std Step Trials= 20
Max Error Tol= 0.3
Flow Tol Ratio= 0.001
Split Flow NTrial= 30
Split Flow Tol= 0.02
Split Flow Ratio= 0.02
Log Output Level= 0
Friction Slope Method= 1
Unsteady Friction Slope Method= 2
Unsteady Bridges Friction Slope Method= 1
Parabolic Critical Depth
Global Vel Dist= 0 , 0 , 0
Global Log Level= 0
CheckData=True
Encroach Param=-1 ,0,0, 0
Computation Interval=0.1SEC
Output Interval=1MIN
Instantaneous Interval=Max Profile
Mapping Interval=1HOUR
Computation Time Step Use Courant=        0
Computation Time Step Use Time Series=    0
Computation Time Step Count To Double=0
Computation Time Step Max Doubling=0
Computation Time Step Max Halving=0
Computation Time Step Residence Courant=0
Run HTab= 0
Run UNet= 0
Run Sediment= 0
Run PostProcess= 0
Run WQNet= 0
Run RASMapper= 0
UNET Theta= 0
UNET Theta Warmup= 0
UNET ZTol= 0
UNET ZSATol= 0
UNET MxIter= 0
UNET Max Iter WO Improvement= 0
UNET MaxInSteps= 0
UNET DtIC= 0
UNET DtMin= 0
UNET MaxCRTS= 0
UNET WFStab= 0
UNET SFStab= 0
UNET WFX= 1
UNET SFX= 1
UNET 1D Methodology=Finite Difference
UNET DSS MLevel= 1
UNET Pardiso=0
UNET DZMax Abort= 0
UNET Use Existing IB Tables= 0
UNET Froude Reduction=False
UNET Froude Limit= 0
UNET Froude Power= 0
UNET D1 Cores= 0
UNET D2 Coriolis=0
UNET D2 Cores= 0
UNET D2 Theta= 1
UNET D2 Theta Warmup= 1
UNET D2 Z Tol= 0.01
UNET D2 Volume Tol= 0.01
UNET D2 Max Iterations= 20
UNET D2 Equation= 0
UNET D2 RampUpFraction=0.1
UNET D2 TimeSlices= 1
UNET D2 BCVolumeCheck=0
UNET D1D2 MaxIter= 0
UNET D1D2 ZTol=0.01
UNET D1D2 QTol=0.1
UNET D1D2 MinQTol=1
DSS File=dss
Write IC File= 0
Write IC File at Fixed DateTime=0
Write IC File at Sim End=0
Echo Input=False
Echo Parameters=False
Echo Output=False
Write Detailed= 0
HDF Write Warmup=0
HDF Write Time Slices=0
HDF Flush=0
HDF Face Node Velocities=0
HDF Compression= 1
HDF Chunk Size= 1
HDF Spatial Parts= 1
HDF Use Max Rows=0
HDF Fixed Rows= 1
Calibration Method= 0
Calibration Iterations= 20
Calibration Max Change=0.05
Calibration Tolerance=0.2
Calibration Maximum=1.5
Calibration Minimum=0.5
Calibration Optimization Method= 1
WQ AD Non Conservative
WQ ULTIMATE=-1
WQ Max Comp Step=1HOUR
WQ Output Interval=15MIN
WQ Output Selected Increments= 0
WQ Output face flow=0
WQ Output face velocity=0
WQ Output face area=0
WQ Output face dispersion=0
WQ Output cell volume=0
WQ Output cell surface area=0
WQ Output cell continuity=0
WQ Output cumulative cell continuity=0
WQ Output face conc=0
WQ Output face dconc_dx=0
WQ Output face courant=0
WQ Output face peclet=0
WQ Output face adv mass=0
WQ Output face disp mass=0
WQ Output cell mass=0
WQ Output cell source sink temp=0
WQ Output nsm pathways=0
WQ Output nsm derived pathways=0
WQ Output MaxMinRange=-1
WQ Daily Max Min Mean=-1
WQ Daily Range=0
WQ Daily Time=0
WQ Create Restart=0
WQ Fixed Restart=0
WQ System Summary=0
WQ Write To DSS=0
WQ Use Fixed Temperature=0
Sorting and Armoring Iterations= 10
XS Update Threshold= 0.02
Bed Roughness Predictor= 0
Hydraulics Update Threshold= 0.02
Energy Slope Method= 1
Volume Change Method= 1
Sediment Retention Method= 0
XS Weighting Method= 0
Number of US Weighted Cross Sections= 1
Number of DS Weighted Cross Sections= 1
Upstream XS Weight=0
Main XS Weight=1
Downstream XS Weight=0
Number of DS XS's Weighted with US Boundary= 1
Upstream Boundary Weight= 1
Weight of XSs Associated with US Boundary= 0
Number of US XS's Weighted with DS Boundary= 1
Downstream Boundary Weight= 0.5
Weight of XSs Associated with DS Boundary= 0.5
Percentile Method= 0
Sediment Output Level= 3
Mass or Volume Output= 0
Output Increment Type= 1
Profile and TS Output Increment= 1
XS Output Flag= 0
XS Output Increment= 10
Write Gradation File= 0
Read Gradation Hotstart= 0
Write HDF5 File= 1
Write Binary Output= 1
Write DSS Sediment File= 0
SV Curve= 0
Specific Gage Flag= 0

--- HNGRDCK_2.f01 (steady flow) ---

Flow Title=Flows
Program Version=5.07
Number of Profiles= 6
Profile Names=01pct,10pct,04pct,02pct,0_2pct,01plus
River Rch & RM=HNGRDCK_2,Main            ,20041
     435     227     304     367     610     643
River Rch & RM=HNGRDCK_2,Main            ,19595
     612     324     431     518     854     905
River Rch & RM=HNGRDCK_2,Main            ,18124
     685     364     483     580     953    1012
River Rch & RM=HNGRDCK_2,Main            ,16607
     789     422     558     669    1095    1166
River Rch & RM=HNGRDCK_2,Main            ,13894
     878     472     623     746    1217    1299
River Rch & RM=HNGRDCK_2,Main            ,10055
     976     527     694     830    1350    1444
River Rch & RM=HNGRDCK_2,Main            ,6385
    1091     591     777     929    1506    1614
River Rch & RM=HNGRDCK_2,Main            ,1
    2086    1159    1505    1786    2845    3086
Boundary for River Rch & Prof#=HNGRDCK_2,Main            , 1
Up Type= 0
Dn Type= 1
Dn Known WS=1696.2
Boundary for River Rch & Prof#=HNGRDCK_2,Main            , 2
Up Type= 0
Dn Type= 1
Dn Known WS=1694.5
Boundary for River Rch & Prof#=HNGRDCK_2,Main            , 3
Up Type= 0
Dn Type= 1
Dn Known WS=1695.2
Boundary for River Rch & Prof#=HNGRDCK_2,Main            , 4
Up Type= 0
Dn Type= 1
Dn Known WS=1695.8
Boundary for River Rch & Prof#=HNGRDCK_2,Main            , 5
Up Type= 0
Dn Type= 1
Dn Known WS=1696.9
Boundary for River Rch & Prof#=HNGRDCK_2,Main            , 6
Up Type= 0
Dn Type= 1
Dn Known WS=1697.1
DSS Import GetInterval= 0
DSS Import GetPeak= 0
DSS Import FillOption= 0

--- HNGRDCK_2.g01 (geometry) ---

Geom Title=Geometry
Program Version=5.07

River Reach=HNGRDCK_2       ,Main
Reach XY= 30
     2035667.276264901.994000045     2035791.058 264662.81099997
2035734.90700003264115.4950000412036074.99600003263505.425000029
     2036026.902263026.9930000592036977.66600001261854.818000015
2037120.72200001261094.7480000322037431.28599999260644.569000024
     2037586.867259166.7970000522037427.32800001258844.037000008
 2037612.7066521258585.932301396     2037576.451258361.241000047
2038133.74299999257824.782999982     2038118.284257435.629000013
2038542.59700002257178.9489999852038580.07100002256821.571000035
2038888.02400002256604.0310000272039277.78699999256740.591000008
2039781.25899999256617.9780000312039998.03000001256416.211000019
2040212.50899999256536.7320000112041732.22700001 255824.10800002
2041787.21200002254748.482999979     2042514.549 253960.73300003
2043008.20565304253659.8938918182043033.35900001253060.453000043
2043820.97299999 252453.48100003     2044758.473253027.483000027
2045126.31100001252927.6569999532045434.90692672252586.942787626

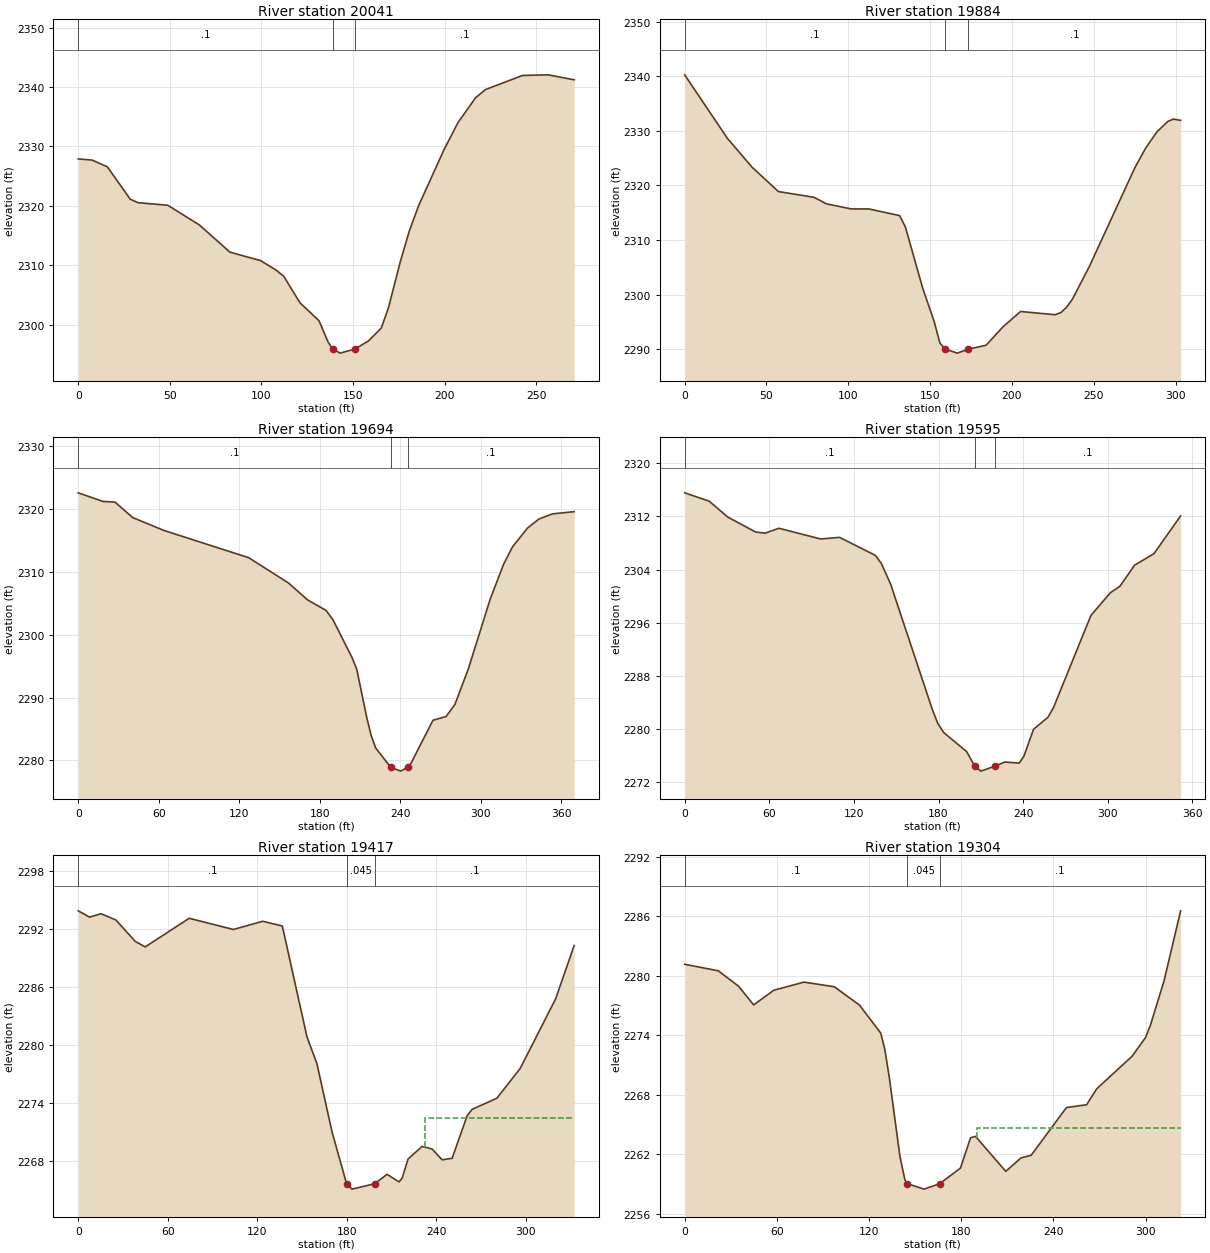
Type RM Length L Ch R = 1 ,20041   ,162.5,156.6,150.7
XS GIS Cut Line= 4
2035786.88855268264986.9560095472035701.18358327264919.294191588
2035633.52176531264859.1503534032035577.11929315264816.284474566
#Sta/Elev= 30
       0  2327.9     7.5 2327.71    15.9 2326.57    28.4 2321.12    32.6 2320.54
    48.9  2320.1    66.1 2316.79    82.8 2312.21    99.5 2310.79   107.9 2309.21
   112.2 2308.13     121 2303.69   131.4 2300.67   136.3 2297.11   138.82295.912
   142.9 2295.22     1512295.905   158.4 2297.28   165.4 2299.46   169.2 2302.77
   175.8 2310.66   180.7  2315.8   185.7    2320   199.7 2329.52   207.2    2334
   216.8 2338.19   222.3 2339.58   242.4 2341.94   256.4 2342.05   270.6 2341.21
#Mann= 3 ,-1 , 0
       0      .1       0   138.8    .045       0     151      .1       0
Bank Sta=138.8,151
XS Rating Curve= 0 ,0
Exp/Cntr(USF)=0,0
Exp/Cntr=0.3,0.1

Type RM Length L Ch R = 1 ,19884   ,196.7,190.2,182.8
XS GIS Cut Line= 4
2035911.68701692264845.6179898122035804.93170414264783.970555672
  2035677.126048264734.3518891692035635.63437124264724.113683217
#Sta/Elev= 30
       0 2340.25    26.1 2328.63    41.1 2323.37    57.3 2318.88      79 2317.84
    86.5 2316.65   101.7 2315.71   112.6  2315.7   131.4 2314.48   134.9 2312.39
   145.5 2301.16   152.5 2295.08     156 2291.13   159.42290.029   166.6 2289.31
   173.2 2290.02   184.2 2290.76   194.7 2294.17   205.3 2296.93   226.4 2296.34
   229.9 2296.73   233.4  2297.7     237  2299.2   247.5 2305.28   275.2 2323.29
   281.8 2326.88   288.7 2329.84   295.3 2331.73   298.7 2332.14   303.1 2331.92
#Mann= 3 ,-1 , 0
       0      .1       0   159.4    .045       0   173.2      .1       0
Bank Sta=159.4,173.2
XS Rating Curve= 0 ,0
Exp/Cntr(USF)=0,0
Exp/Cntr=0.3,0.1

Type RM Length L Ch R = 1 ,19694   ,102.8,99.6,95.4
XS GIS Cut Line= 4
2035946.26972387264734.3518891692035804.93170414264582.488697752
  2035710.205159264586.9994856162035643.48437344 264595.33958381
#Sta/Elev= 30
       0 2322.58    18.5 2321.21    27.4 2321.11    40.6 2318.64    63.8  2316.6
     127 2312.26   156.7 2308.23   170.8 2305.56   184.6 2303.88   189.7 2302.43
   204.1 2296.33   207.5 2294.53     215 2286.81   218.3 2283.95   221.6 2281.99
   232.8 2278.92   240.3  2278.3   245.52278.935   247.9 2279.53   264.3 2286.39
   274.1 2286.99   280.7 2288.93   290.6 2294.52     307 2305.69   316.9  2311.2
   323.5 2313.96   334.9 2317.01   343.4 2318.43   353.3 2319.23   369.5 2319.58
#Mann= 3 ,-1 , 0
       0      .1       0   232.8    .045       0   245.5      .1       0
Bank Sta=232.8,245.5
XS Rating Curve= 0 ,0
Exp/Cntr(USF)=0,0
Exp/Cntr=0.3,0.1

Type RM Length L Ch R = 1 ,19595   ,166.4,178,184
XS GIS Cut Line= 4
2035968.82366319264457.6902335182035804.93170414264475.733384973
2035686.14762372264507.308900021 2035625.0645818264526.153668274
#Sta/Elev= 30
       0 2315.56    17.4  2314.3    30.6  2311.9    50.4 2309.65      57 2309.48
    66.9 2310.22    96.5  2308.6   109.8 2308.85   135.2 2306.14   139.5 2304.91
   146.1 2301.77   175.6 2282.92   179.5 2280.81   183.7 2279.43   199.9 2276.58
   205.72274.374     210 2273.62   219.92274.361     227 2274.99   237.2 2274.83
   240.6 2275.89   247.4 2279.93   257.6 2281.73   261.5 2283.17   288.1 2297.08
   301.9 2300.51   308.7 2301.49     319 2304.65   332.8 2306.39   351.7 2312.08
#Mann= 3 ,-1 , 0
       0      .1       0   205.7    .045       0   219.9      .1       0
Bank Sta=205.7,219.9
XS Rating Curve= 0 ,0
Exp/Cntr(USF)=0,0
Exp/Cntr=0.3,0.1

Type RM Length L Ch R = 1 ,19417   ,117.6,112.9,107.4
XS GIS Cut Line= 4
2035917.70140074264331.3881733292035770.34899718264335.898961193
2035650.06132081264310.3378299642035588.10493374264313.219522386
#Sta/Elev= 30
       0 2293.92     7.6 2293.27    15.3 2293.62    25.2 2292.98    38.3 2290.75
    44.9 2290.19    74.4 2293.15     104 2291.99   123.7 2292.84   136.8 2292.35
   153.3  2280.9     160 2278.11   170.1 2271.07   179.92265.688   183.5 2265.14
   198.82265.706     207 2266.67     215 2265.89   217.1 2266.27   221.1 2268.26
   230.5 2269.56   237.2 2269.29   243.9 2268.17   250.6 2268.33   260.7 2272.73
     264 2273.39   280.6 2274.54   296.2 2277.61     320 2284.82   332.4 2290.33
#Mann= 3 ,-1 , 0
       0      .1       0   179.9    .045       0   198.8      .1       0
#XS Ineff= 2 , 0
                          232.26          2272.5
Permanent Ineff=
       F       T
Bank Sta=179.9,198.8
XS Rating Curve= 0 ,0
Exp/Cntr(USF)=0,0
Exp/Cntr=0.3,0.1

Type RM Length L Ch R = 1 ,19304   ,96.4,99.2,103.1
XS GIS Cut Line= 4
2035901.33564671264212.9667837762035777.03547417264214.742500527
 2035593.2487905264223.6210842792035579.09892121 264226.88643873
#Sta/Elev= 30
       0 2281.14    21.9 2280.48    35.1 2278.92    44.9 2277.04      58 2278.52
    77.7 2279.34    97.4 2278.87   113.8 2277.02   127.6  2274.2   130.2 2272.61
   133.1 2269.82   140.1 2261.77   143.4 2259.36     1452259.005   155.8 2258.46
     1662259.013   179.5 2260.58   186.1 2263.65   189.3 2263.78     209 2260.25
   218.9 2261.61   225.5 2261.87   248.5 2266.69   261.6 2266.97   268.2 2268.58
   291.2 2271.86     300 2273.76   303.1 2274.97     312 2279.46   322.8 2286.53
#Mann= 3 ,-1 , 0
       0      .1       0     145    .045       0     166      .1       0
#XS Ineff= 2 , 0
                          189.96         2264.67
Permanent Ineff=
       F       F
Bank Sta=145,166
XS Rating Curve= 0 ,0
Exp/Cntr(USF)=0,0
Exp/Cntr=0.3,0.1

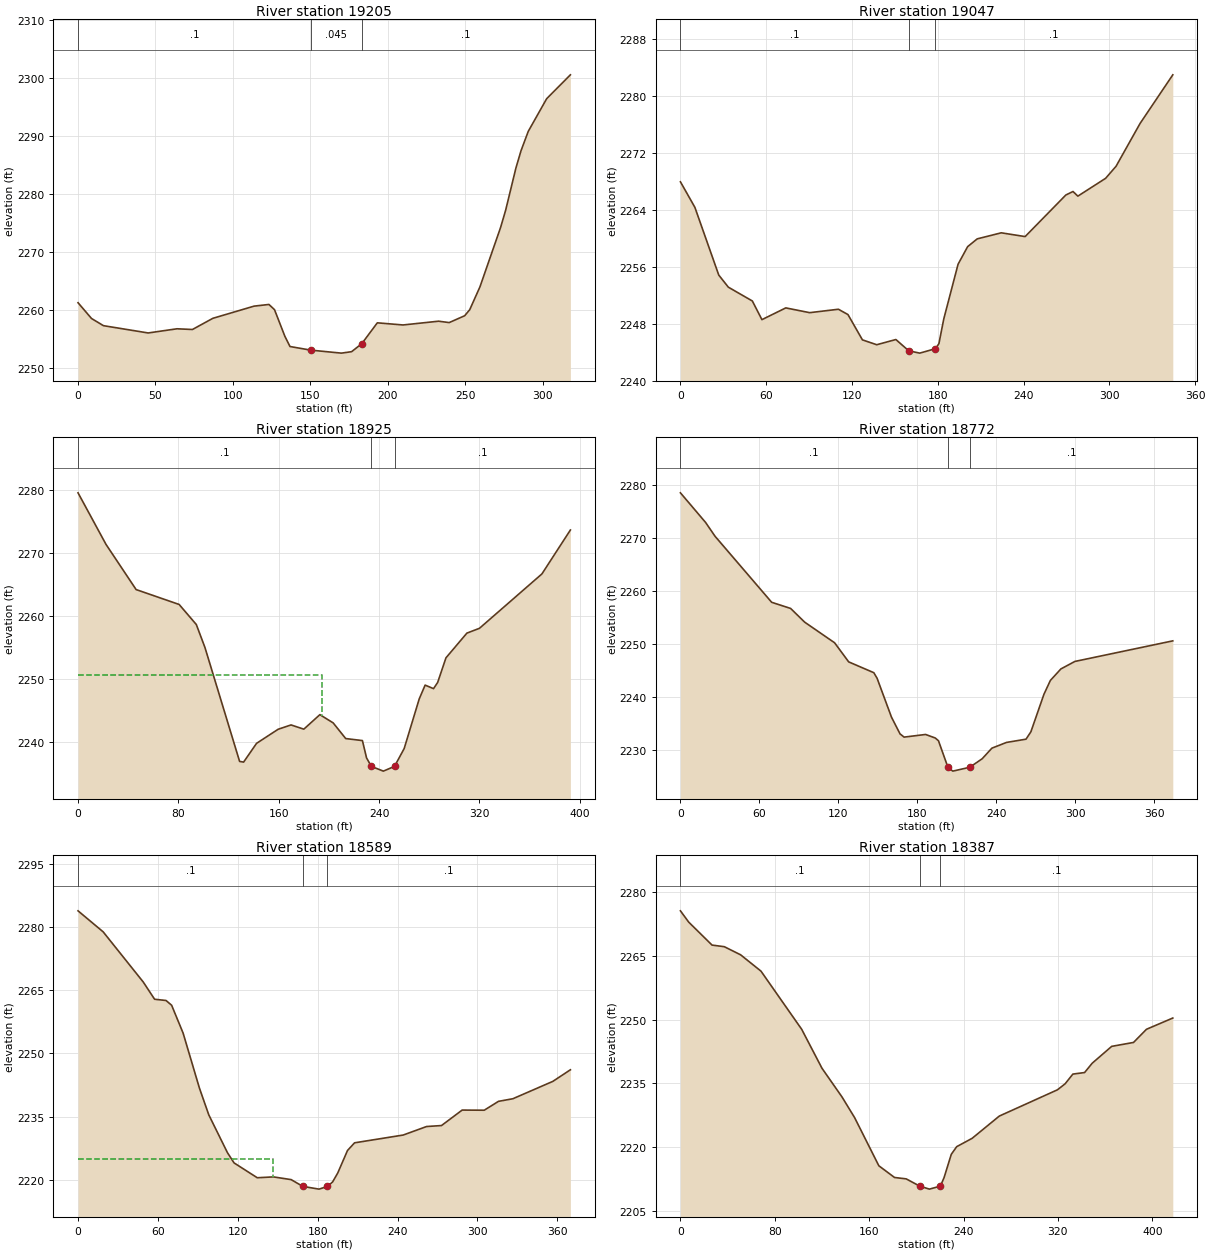
Type RM Length L Ch R = 1 ,19205   ,153.4,157.6,152.8
XS GIS Cut Line= 2
2035899.99216589264144.6857826712035585.40883261264098.158004895
#Sta/Elev= 30
       0 2261.25     8.7 2258.53    16.4 2257.29    45.3 2256.03    63.9 2256.75
    73.9 2256.63    87.1 2258.56   113.7 2260.66   123.3 2260.95   126.9 2260.05
   133.6 2255.45   136.9 2253.69   150.2 2253.07   170.1 2252.55   176.7  2252.8
   183.3 2254.19   193.3 2257.78   209.9 2257.41   232.9 2258.06   239.7 2257.82
   249.7    2259     253 2260.05   259.6    2264   272.9 2274.22   276.2 2277.23
   282.8 2284.48   286.1 2287.47   290.8 2290.83   302.7 2296.47     318 2300.58
#Mann= 3 ,-1 , 0
       0      .1       0   150.2    .045       0   183.3      .1       0
Bank Sta=150.2,183.3
XS Rating Curve= 0 ,0
Exp/Cntr(USF)=0,0
Exp/Cntr=0.3,0.1

Type RM Length L Ch R = 1 ,19047   ,121.1,122,120
XS GIS Cut Line= 2
2035981.14085418264034.8811530472035643.64085418263966.131153062
#Sta/Elev= 30
       0 2267.92    10.1 2264.34    26.8 2254.83    33.5 2253.13    50.3 2251.19
      57 2248.57    73.7 2250.22    90.4 2249.55   110.5 2250.03   117.2 2249.28
   127.3 2245.73   137.3 2245.05   150.7 2245.78   159.72244.193   167.4 2243.87
   178.42244.495   180.8  2245.2   184.2 2248.67   194.2 2256.35   200.9 2258.82
   207.6 2259.91   224.4 2260.76   241.1 2260.23   269.6 2266.07   274.6 2266.56
     278 2265.91   297.4 2268.41   304.7  2270.1   321.5 2276.11   344.4 2282.94
#Mann= 3 ,-1 , 0
       0      .1       0   159.7    .045       0   178.4      .1       0
Bank Sta=159.7,178.4
XS Rating Curve= 0 ,0
Exp/Cntr(USF)=0,0
Exp/Cntr=0.3,0.1

Type RM Length L Ch R = 1 ,18925   ,149.1,153.1,161.1
XS GIS Cut Line= 4
2036054.93514563263944.8335544512035882.69062083263892.449910312
2035717.54896303263863.150583928  2035673.048602263858.382688103
#Sta/Elev= 30
       0  2279.5    22.3 2271.33    46.3 2264.17    80.6 2261.81    94.3 2258.63
   101.2 2254.98   128.8 2236.94     132 2236.83   142.3  2239.8   159.5 2242.03
   169.8 2242.72     180 2242.05   192.8 2244.35   203.4 2243.04   213.4 2240.56
   226.7 2240.24     230  2237.5   233.82236.152   243.4  2235.4   252.32236.152
     260 2238.98     272 2246.85   276.7 2249.03   283.4 2248.47   286.7 2249.46
   293.3 2253.35     310 2257.27     320 2258.03   369.8 2266.65   392.5 2273.61
#Mann= 3 ,-1 , 0
       0      .1       0   233.8    .045       0   252.3      .1       0
#XS Ineff= 2 , 0
           194.3 2250.68
Permanent Ineff=
       F       F
Bank Sta=233.8,252.3
XS Rating Curve= 0 ,0
Exp/Cntr(USF)=0,0
Exp/Cntr=0.3,0.1

Type RM Length L Ch R = 1 ,18772   ,180.6,182.5,183.5
XS GIS Cut Line= 4
2036090.44948064263837.4026910462035939.51355684263770.813312903
2035799.23193356263697.1210677572035750.56849868263683.486915744
#Sta/Elev= 30
       0 2278.56    19.1 2272.98    26.3 2270.37    69.3 2257.93    83.7 2256.77
    94.4 2254.18   117.1  2250.3   127.8  2246.7   146.9 2244.66   149.4  2243.6
   160.3 2236.29   166.8 2233.13   169.9 2232.52   186.2 2233.02   193.5 2232.36
     196 2231.84   203.2 2226.82   203.2 2226.81   206.9 2226.11   219.8 2226.84
   229.2 2228.44   236.6 2230.44   247.7 2231.52   262.5 2232.13   266.2 2233.52
   276.1 2240.58     281  2243.2     289 2245.37   299.6 2246.78     374 2250.66
#Mann= 3 ,-1 , 0
       0      .1       0   203.2    .045       0   219.8      .1       0
Bank Sta=203.2,219.8
XS Rating Curve= 0 ,0
Exp/Cntr(USF)=0,0
Exp/Cntr=0.3,0.1

Type RM Length L Ch R = 1 ,18589   ,209.8,202.6,191.1
XS GIS Cut Line= 4
2036140.16954965 263705.999651512036050.49585375263631.419547989
2035878.25132895263521.3251094582035830.28962913263512.683361742
#Sta/Elev= 30
       0 2283.95    18.9 2278.94      49    2267    57.5 2262.91    66.1 2262.61
    70.3 2261.48    78.9 2254.87    91.2 2241.74    98.2  2235.4   112.2 2226.41
   117.2 2223.96   134.6 2220.43   146.8 2220.63   160.1 2219.98   168.82218.374
     181 2217.72   187.3 2218.36   191.2 2219.43   195.1 2221.58   202.4 2226.92
   207.7 2228.74   244.2 2230.59   261.8 2232.62     273 2232.85   288.5 2236.53
   305.1  2236.5   315.8 2238.61   326.6 2239.23   356.6 2243.36   369.8 2246.12
#Mann= 3 ,-1 , 0
       0      .1       0   168.8    .045       0   187.3      .1       0
#XS Ineff= 2 , 0
           146.8    2225
Permanent Ineff=
       F       F
Bank Sta=168.8,187.3
XS Rating Curve= 0 ,0
Exp/Cntr(USF)=0,0
Exp/Cntr=0.3,0.1

Type RM Length L Ch R = 1 ,18387   ,124,123.4,123.9
XS GIS Cut Line= 4
2036249.37612981263490.2500663242036089.56162226263437.866422185
2035964.37359135263428.9878384322035840.64748756263426.349130057
#Sta/Elev= 30
       0 2275.59       7 2272.94    26.8 2267.53    37.2 2267.15      51 2265.25
    68.3  2261.4   102.8 2247.72     120 2238.56     137  2231.8   147.7 2226.93
   168.2 2215.62   181.5 2212.87   191.4 2212.54   202.82210.844   211.1 2210.13
   220.4 2210.85   223.5 2212.84   229.6 2218.31   234.2 2220.12   247.3 2222.08
   270.3 2227.31   319.6 2233.49   326.1  2234.9   332.7 2237.19   342.6 2237.55
   349.1 2239.75   365.6 2243.71   384.1 2244.63   395.1 2247.73   417.4 2250.37
#Mann= 3 ,-1 , 0
       0      .1       0   202.8    .045       0   220.4      .1       0
Bank Sta=202.8,220.4
XS Rating Curve= 0 ,0
Exp/Cntr(USF)=0,0
Exp/Cntr=0.3,0.1

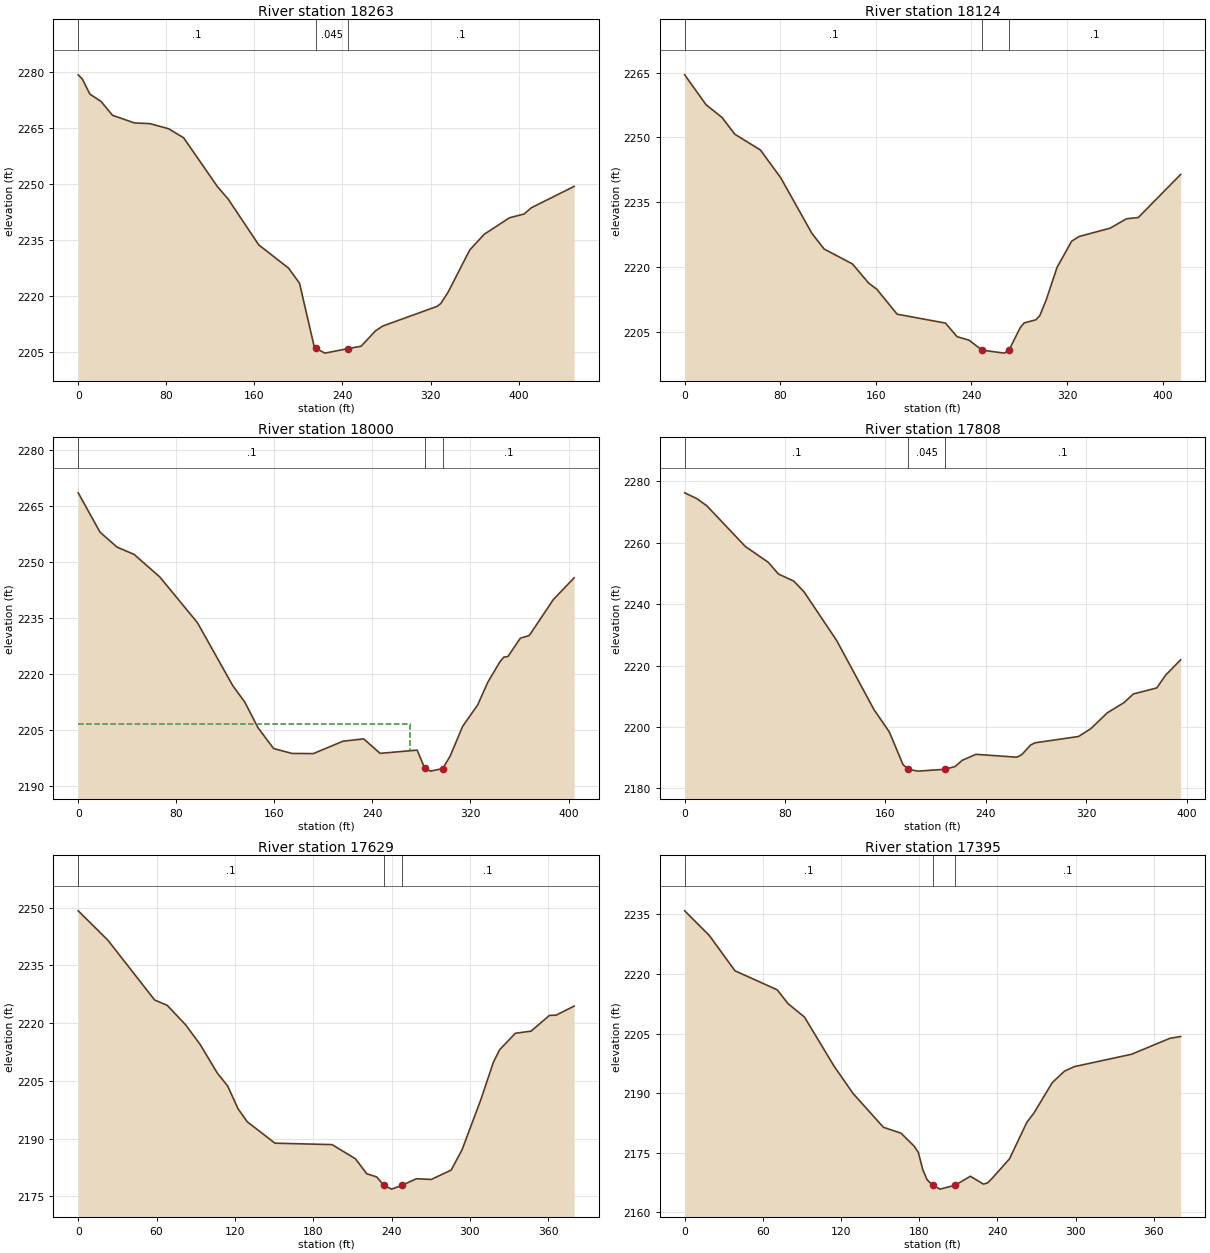
Type RM Length L Ch R = 1 ,18263   ,141,139,137
XS GIS Cut Line= 4
2036296.43262369 263369.501327292036117.08523189263318.893399901
2035960.82215785263307.3512410232035853.66965619263313.423216117
#Sta/Elev= 30
       0 2279.33     3.8 2278.17    10.6 2274.17    20.8 2272.18    31.1  2268.5
    51.1 2266.44    65.2 2266.25    82.2 2264.87    95.8 2262.44   126.5 2249.35
   136.2 2246.03     164 2233.75   191.1 2227.52     201 2223.48   214.1 2206.79
   216.22206.021     224 2204.76     245 2205.97   256.9 2206.61   270.1 2210.76
   276.6 2212.02     326  2217.3   329.3 2218.06   335.9 2221.08   355.6 2232.41
   368.7  2236.6   391.7 2241.03   404.9 2242.03   411.4 2243.69   450.4 2249.44
#Mann= 3 ,-1 , 0
       0      .1       0   216.2    .045       0     245      .1       0
Bank Sta=216.2,245
XS Rating Curve= 0 ,0
Exp/Cntr(USF)=0,0
Exp/Cntr=0.3,0.1

Type RM Length L Ch R = 1 ,18124   ,118.3,124.7,129.4
XS GIS Cut Line= 4
2036274.23616431263238.9861461292036075.35588826263185.714643614
2035938.62569847263196.3689441172035867.30250777263205.712593554
#Sta/Elev= 30
       0  2264.5    17.9 2257.57    31.3 2254.61    41.9 2250.75    63.4 2247.08
    80.3 2240.68   106.5 2227.75   116.7 2224.14   140.4 2220.68     154 2216.24
   160.8 2214.82   177.8 2209.04   218.2 2206.98     228 2203.82   237.9 2203.03
   248.9 2200.71   267.5 2200.02   271.42200.725   280.7 2205.88     284 2207.01
   293.8 2207.74   297.1 2208.67   302.5 2212.33   311.6 2219.88   323.8 2225.95
     330 2227.04     356 2228.97   369.7 2231.15   379.6 2231.44     415 2241.42
#Mann= 3 ,-1 , 0
       0      .1       0   248.9    .045       0   271.4      .1       0
Bank Sta=248.9,271.4
XS Rating Curve= 0 ,0
Exp/Cntr(USF)=0,0
Exp/Cntr=0.3,0.1

Type RM Length L Ch R = 1 ,18000   ,191.6,191.6,193.3
XS GIS Cut Line= 4
2036296.43262369263155.5274588562036095.77663089263084.498788836
2035922.64424772263045.4330203252035908.68518872263042.561442475
#Sta/Elev= 30
       0 2268.44    17.8 2257.92    31.7 2253.92    45.6 2251.97    66.5 2245.96
    97.3 2233.69     126 2216.91   135.9 2212.47   146.6 2205.65   159.4 2200.05
   174.4 2198.73   191.8 2198.69   216.1 2202.01   232.9 2202.63   246.3 2198.75
   276.5 2199.62   282.82194.712   287.5    2194   297.42194.691   303.5 2198.06
   313.6 2205.96   325.9 2211.71   334.1 2217.74   343.9 2223.17   347.2 2224.49
   350.6 2224.66   360.7 2229.56     368 2230.27   387.6 2239.88   404.6 2245.71
#Mann= 3 ,-1 , 0
       0      .1       0   282.8    .045       0   297.4      .1       0
#XS Ineff= 2 , 0
             271 2206.67
Permanent Ineff=
       T       F
Bank Sta=282.8,297.4
XS Rating Curve= 0 ,0
Exp/Cntr(USF)=0,0
Exp/Cntr=0.3,0.1

Type RM Length L Ch R = 1 ,17808   ,181.8,178.8,177.3
XS GIS Cut Line= 4
 2036307.0869242263051.6480289522036183.67461004262961.086474676
  2036055.823004262899.8242467842035956.03523601262888.354388394
#Sta/Elev= 30
       0 2276.28     9.6 2274.42    17.7 2272.04    48.3 2258.81    66.6 2253.66
    74.7 2249.84    86.9 2247.53    95.1 2244.05   121.1 2228.19     151 2205.57
   163.1 2198.38     174 2187.75   178.22186.197     186  2185.6   207.42186.195
   215.5  2187.1   221.3 2189.13   232.2 2191.08   264.7 2190.14   268.6 2190.93
   275.8 2194.13   279.4 2194.84   313.9 2196.88   323.7 2199.43     337 2204.64
   350.2 2207.93   357.6 2210.74   376.3 2212.71   383.3 2216.85   395.3 2221.86
#Mann= 3 ,-1 , 0
       0      .1       0   178.2    .045       0   207.4      .1       0
Bank Sta=178.2,207.4
XS Rating Curve= 0 ,0
Exp/Cntr(USF)=0,0
Exp/Cntr=0.3,0.1

Type RM Length L Ch R = 1 ,17629   ,219.3,234.6,246.8
XS GIS Cut Line= 4
2036340.82554246 262904.263538662036182.78675166 262794.16910013
2036097.55234764262744.4490311162036020.83447366262700.278133977
#Sta/Elev= 30
       0 2249.17    22.6 2241.59    58.5 2226.01    68.2  2224.6    82.4  2219.5
    93.6 2214.32   106.5 2207.02   114.5 2203.63   122.4 2197.73   129.5 2194.34
   150.7 2188.79   194.4 2188.42   212.3 2184.74     221 2180.84   228.6 2180.02
   234.12177.837     240 2176.85   247.92177.834     259 2179.55   270.4 2179.37
   285.6 2181.79   293.9 2187.05   308.3 2200.06   317.9 2209.77   322.7 2213.07
   334.8 2217.35   346.8 2217.91   360.9 2221.99     366 2222.06   379.8 2224.41
#Mann= 3 ,-1 , 0
       0      .1       0   234.1    .045       0   247.9      .1       0
Bank Sta=234.1,247.9
XS Rating Curve= 0 ,0
Exp/Cntr(USF)=0,0
Exp/Cntr=0.3,0.1

Type RM Length L Ch R = 1 ,17395   ,198.8,182.7,168.9
XS GIS Cut Line= 4
2036386.10631959262860.7584782732036327.50766683262716.925421483
2036308.86264095262607.7188413282036218.68413549262537.324395738
#Sta/Elev= 30
       0 2235.92    18.9 2229.72    38.6 2220.82      71 2216.03    79.3 2212.55
    91.9 2209.17   114.5 2196.87   129.1 2189.96   152.5 2181.41     166 2179.93
     176 2176.67   179.3 2175.07   182.6 2170.83     186  2168.2   190.32166.801
   195.9 2165.84   207.4 2166.81   219.2 2169.08   229.2 2167.11   232.5 2167.43
   235.9 2168.56   249.2 2173.46   262.5 2182.65     268 2185.02     282 2192.65
   291.4 2195.55     299 2196.69   342.8  2199.8   372.3 2203.82   380.5 2204.27
#Mann= 3 ,-1 , 0
       0      .1       0   190.3    .045       0   207.4      .1       0
Bank Sta=190.3,207.4
XS Rating Curve= 0 ,0
Exp/Cntr(USF)=0,0
Exp/Cntr=0.3,0.1

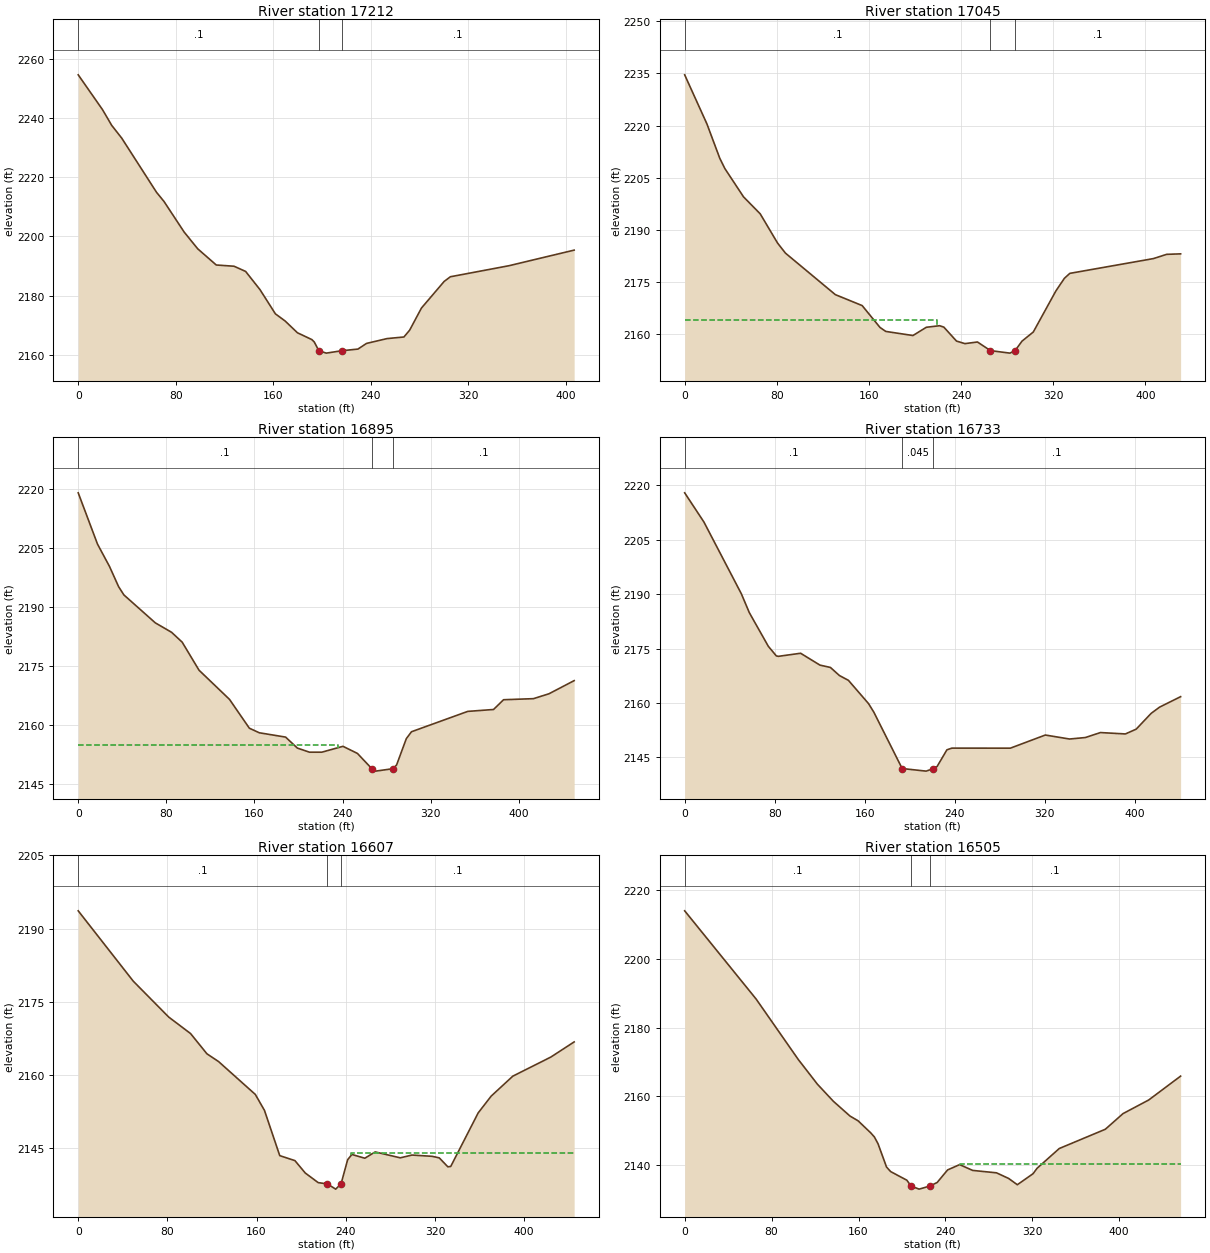
Type RM Length L Ch R = 1 ,17212   ,172,166.9,167.4
XS GIS Cut Line= 4
2036603.63162153262718.7011382342036528.16365963 262616.59742508
2036384.33060284262518.0451454272036285.04491897262482.788596459
#Sta/Elev= 30
       0 2254.67    19.9 2242.91    27.5 2237.56    35.7 2233.25    64.2 2214.95
    70.4 2211.81    86.9 2201.48      98 2195.83   113.2 2190.35   127.8 2189.93
   137.3 2188.17   149.1    2182   161.7 2173.83   169.7  2171.4   179.8 2167.42
   191.6 2165.12   193.6  2164.3   197.32161.375   203.4 2160.54     2162161.338
   229.4 2161.91   236.4 2163.82   253.2 2165.45   267.1    2166   271.8  2168.3
   281.5  2175.8   300.1 2184.79   305.2 2186.37   353.2  2190.1   406.7 2195.38
#Mann= 3 ,-1 , 0
       0      .1       0   197.3    .045       0     216      .1       0
Bank Sta=197.3,216
XS Rating Curve= 0 ,0
Exp/Cntr(USF)=0,0
Exp/Cntr=0.3,0.1

Type RM Length L Ch R = 1 ,17045   ,145,149.7,154.9
XS GIS Cut Line= 4
2036694.19317581  262597.95239922036552.13583577262438.137891655
2036436.71424698262381.3149556392036352.18278241262356.416596985
#Sta/Elev= 30
       0  2234.6    19.3  2220.5    30.5 2210.59    34.9 2207.65    51.1 2199.52
    65.6 2194.63    80.7 2186.21    87.5 2183.34   130.8 2171.41   154.1 2168.26
   169.6 2161.97   174.6 2160.83   198.2 2159.65   209.8 2162.02   221.3 2162.47
     225 2162.07     236 2158.06   243.3 2157.32   254.2 2157.79   265.52155.311
   282.4 2154.59   286.9 2155.32   292.9 2158.04   302.7 2160.67   322.3 2172.47
   329.7  2176.1   334.4 2177.52     407 2181.77   418.5 2182.99   430.6 2183.13
#Mann= 3 ,-1 , 0
       0      .1       0   265.5    .045       0   286.9      .1       0
#XS Ineff= 2 , 0
       0   219.4    2164               0
Permanent Ineff=
       F       F
Bank Sta=265.5,286.9
XS Rating Curve= 0 ,0
Exp/Cntr(USF)=0,0
Exp/Cntr=0.3,0.1

Type RM Length L Ch R = 1 ,16895   ,162.6,162.6,162.1
XS GIS Cut Line= 4
2036760.78255395262475.4279434162036646.24882354262352.903487631
2036490.87360787262217.9490145942036423.70296634262180.702734694
#Sta/Elev= 30
       0 2218.98    17.5 2205.97    28.4 2200.29    36.7 2195.14    41.5 2193.05
      70 2185.96    84.8 2183.56    94.4 2181.06   109.7 2173.94   137.4 2166.52
   155.4 2159.21   164.4 2158.05   188.3 2156.95     199 2154.16     210 2153.12
   221.2 2153.12   240.4 2154.61   253.5 2152.81   266.62148.932     270 2148.31
   285.92148.929   289.1 2149.89   297.9 2156.55   302.6 2158.31   353.7 2163.48
   377.1 2163.96   386.2 2166.44   413.3 2166.71   427.5 2167.96   450.3 2171.29
#Mann= 3 ,-1 , 0
       0      .1       0   266.6    .045       0   285.9      .1       0
#XS Ineff= 2 , 0
           236.1    2155
Permanent Ineff=
       F       F
Bank Sta=266.6,285.9
XS Rating Curve= 0 ,0
Exp/Cntr(USF)=0,0
Exp/Cntr=0.3,0.1

Type RM Length L Ch R = 1 ,16733   ,127.8,125.6,125.5
XS GIS Cut Line= 4
2036807.83904784262336.9220368772036709.28676818262195.752555212
2036626.71593929262122.9481684422036480.52526576262061.079077937
#Sta/Elev= 30
       0 2217.94    17.1  2209.9    50.4 2190.11    57.5  2184.9    74.4 2175.63
    81.5 2172.99    83.3 2172.87   103.1 2173.72   120.3 2170.45   129.6 2169.81
   137.6 2167.58   145.6 2166.26   163.5 2159.84   168.2 2157.48   193.42141.943
   214.7 2141.23   221.12141.919   224.4 2142.48   233.2 2147.11   237.6 2147.57
   289.6 2147.56   320.7 2151.18   342.2 2150.08   356.3 2150.49   369.7 2151.86
   391.9 2151.48   401.5  2152.8   414.8 2157.15   422.3 2158.87     441 2161.75
#Mann= 3 ,-1 , 0
       0      .1       0   193.4    .045       0   221.1      .1       0
Bank Sta=193.4,221.1
XS Rating Curve= 0 ,0
Exp/Cntr(USF)=0,0
Exp/Cntr=0.3,0.1

Type RM Length L Ch R = 1 ,16607   ,99.5,101.8,106.3
XS GIS Cut Line= 4
2036846.90481635262248.1361993522036774.10042958262102.527425811
2036671.10885805261995.9844207822036558.08901569261924.208786299
#Sta/Elev= 30
       0 2193.63    49.4 2179.22    81.2 2171.87   100.8 2168.49   115.5 2164.34
   125.9 2162.76   158.9 2156.02   167.1 2152.75   180.8 2143.49   194.4 2142.47
   203.7 2139.93   215.3 2137.96   223.52137.696     231 2136.63   235.82137.717
   241.7 2142.65   245.5 2143.73   257.1 2142.96   266.4 2144.25   288.9 2143.04
   299.4 2143.61   317.6 2143.35   323.9 2143.03   331.6  2141.2   334.2 2141.28
   358.8 2152.24   370.5 2155.69   389.9 2159.77     424 2163.68   444.9 2166.78
#Mann= 3 ,-1 , 0
       0      .1       0   223.5    .045       0   235.8      .1       0
#XS Ineff= 2 , 0
                          245.13            2144
Permanent Ineff=
       F       F
Bank Sta=223.5,235.8
XS Rating Curve= 0 ,0
Exp/Cntr(USF)=0,0
Exp/Cntr=0.3,0.1

Type RM Length L Ch R = 1 ,16505   ,150,144.2,140.1
XS GIS Cut Line= 4
2036917.04562799262206.4068557152036847.79267472262066.125232426
 2036751.9039702261892.104990878  2036673.685744261827.689981065
#Sta/Elev= 30
       0 2214.03    65.8 2188.32   104.6 2170.71   122.2 2163.52   136.9 2158.54
   152.2 2154.24   159.6 2152.87   171.2 2149.37   174.6 2148.17     178 2146.16
   185.8  2139.4   189.6 2138.07   204.5 2135.56   208.4 2133.85   215.8 2132.96
   225.42133.832   232.4 2134.89     242 2138.55   253.1  2140.1   265.1 2138.41
     287 2137.71   298.2 2136.07   306.2 2134.24   320.7 2137.46   324.4 2139.04
   344.8 2144.79   387.2  2150.4   403.5 2154.96   427.1 2158.92   456.5 2165.88
#Mann= 3 ,-1 , 0
       0      .1       0   208.4    .045       0   225.4      .1       0
#XS Ineff= 2 , 0
                          253.37         2140.34
Permanent Ineff=
       F       F
Bank Sta=208.4,225.4
XS Rating Curve= 0 ,0
Exp/Cntr(USF)=0,0
Exp/Cntr=0.3,0.1

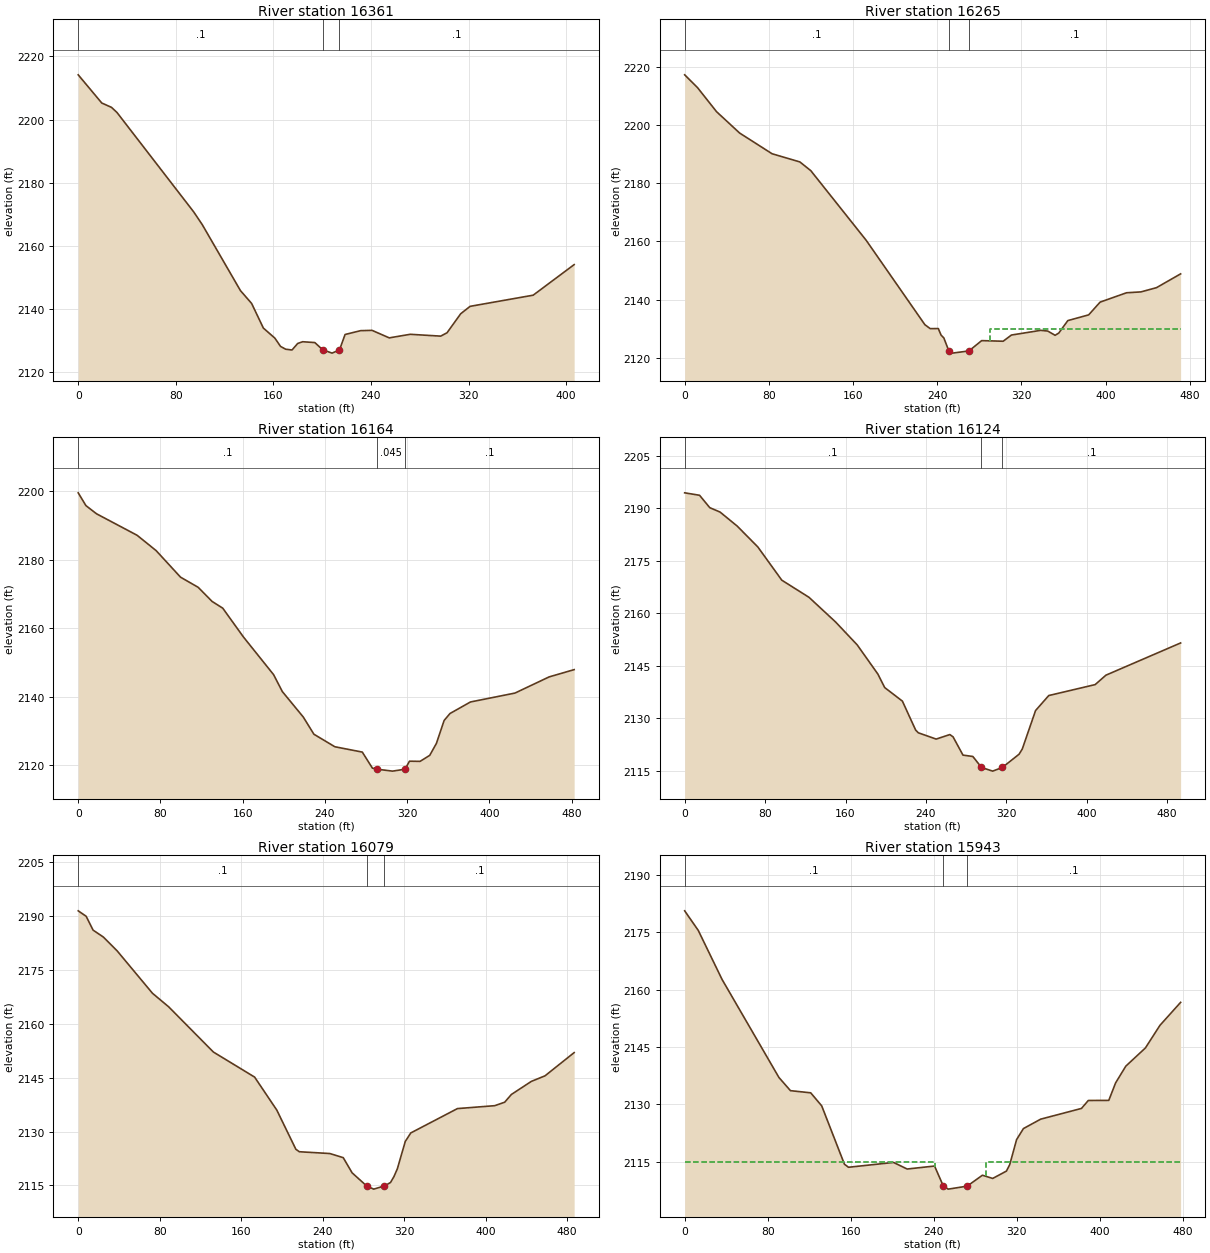
Type RM Length L Ch R = 1 ,16361   ,105.1,96.4,87.2
XS GIS Cut Line= 4
2037034.24293353 262080.330966432036973.86856401261970.236527899
2036851.34410822261845.0484969892036763.61816968261785.805006028
#Sta/Elev= 30
       0 2214.16    19.3 2205.24    27.3 2203.86    31.8 2202.23    94.7 2170.76
   101.7 2166.74     133 2145.86   142.2 2141.77   151.8 2133.99   161.2 2130.82
   165.9 2128.18   170.1  2127.3   175.3 2127.05   179.9 2129.11     184 2129.67
     194  2129.4   200.3 2127.17   208.1 2126.06   214.2 2127.07   218.8 2131.96
   231.5 2133.17   240.9 2133.27     255 2130.89   272.2 2132.02   297.2 2131.44
   302.4 2132.51   313.6 2138.53   321.3 2140.87     373  2144.4   406.6 2154.08
#Mann= 3 ,-1 , 0
       0      .1       0   200.3    .045       0   214.2      .1       0
Bank Sta=200.3,214.2
XS Rating Curve= 0 ,0
Exp/Cntr(USF)=0,0
Exp/Cntr=0.3,0.1

Type RM Length L Ch R = 1 ,16265   ,108.7,100.4,93.2
XS GIS Cut Line= 4
 2037188.0820139261998.8992682072037037.05730427261863.856009332
2036884.43444957261808.7200042292036787.24087451261765.002412234
#Sta/Elev= 30
       0 2217.28    12.2 2212.88    30.3  2204.6    52.3 2197.24    83.1 2190.13
   109.5 2187.32   119.9 2184.31   172.5 2160.38   228.3 2131.35   233.4 2129.98
   241.1 2130.01   243.7 2127.76   246.3 2126.81   251.1 2122.33   254.4 2121.56
   270.22122.316   282.3 2125.86   302.7 2125.65   310.6 2127.78   338.5  2129.4
   345.1 2129.15   352.1 2127.69   355.6 2128.47   364.2 2132.75     384 2134.72
   394.9 2139.11     420 2142.32   433.7 2142.62   448.5 2144.08   471.4 2148.82
#Mann= 3 ,-1 , 0
       0      .1       0   251.1    .045       0   270.2      .1       0
#XS Ineff= 2 , 0
                           289.8            2130
Permanent Ineff=
       F       F
Bank Sta=251.1,270.2
XS Rating Curve= 0 ,0
Exp/Cntr(USF)=0,0
Exp/Cntr=0.3,0.1

Type RM Length L Ch R = 1 ,16164   ,40,40.5,41.7
XS GIS Cut Line= 4
2037294.13724138261815.276970522  2037044.550387261744.248300502
2036935.04785406261746.2213191142036823.30924459261726.282831178
#Sta/Elev= 30
       0 2199.58     7.5 2195.85    17.8 2193.46    57.3 2187.18    75.8  2182.7
    99.6 2174.93   116.7 2171.98   130.3 2167.84   140.6 2165.89   160.9 2157.41
   190.1 2146.46   198.6 2141.52     219 2134.07   229.3 2129.06   249.7  2125.4
   276.4 2123.84   286.2 2119.16     2912118.834   305.8 2118.28   317.92118.837
   322.3 2121.18   332.6 2121.13     342 2122.89   348.5 2126.39     356 2133.08
   361.7 2135.11   381.6 2138.48   424.9 2141.08   458.2 2145.81   482.5 2147.93
#Mann= 3 ,-1 , 0
       0      .1       0     291    .045       0   317.9      .1       0
Bank Sta=291,317.9
XS Rating Curve= 0 ,0
Exp/Cntr(USF)=0,0
Exp/Cntr=0.3,0.1

Type RM Length L Ch R = 1 ,16124   ,40.3,44.7,48.3
XS GIS Cut Line= 4
2037310.90789958261778.7761262072037058.36151729261706.760946881
2036939.98040059261708.733965492 2036828.8361599261692.268152057
#Sta/Elev= 30
       0 2194.39    14.8 2193.69      25 2190.14    35.2  2188.9    52.3 2184.88
    72.8 2178.93    96.6 2169.45   123.7 2164.55   150.2 2157.49   171.7 2150.95
   192.2 2142.64     199 2138.78   216.6 2134.91   229.8 2126.64   232.5 2125.86
   250.2 2124.07   263.8 2125.36     267 2124.71   276.9 2119.49   286.7  2119.1
   295.32115.971   306.4 2114.92     3162115.957   332.7 2119.75   335.9 2121.26
   349.1 2132.22   362.2  2136.5   408.4 2139.63   419.1 2142.32   493.4 2151.52
#Mann= 3 ,-1 , 0
       0      .1       0   295.3    .045       0     316      .1       0
Bank Sta=295.3,316
XS Rating Curve= 0 ,0
Exp/Cntr(USF)=0,0
Exp/Cntr=0.3,0.1

Type RM Length L Ch R = 1 ,16079   ,138.2,136.5,134.9
XS GIS Cut Line= 4
2037320.72805517261730.4108955322037105.77754252 261678.47118058
2036971.53335618261659.2934396742036841.38359366261659.707929364
#Sta/Elev= 30
       0 2191.44     7.8 2189.92    14.6 2186.07    24.7 2184.14    38.2  2180.3
    72.9 2168.49    88.8 2164.72   132.7 2152.13   173.2 2145.15     195 2135.95
   213.7 2125.05   217.1 2124.37     247 2123.87   260.2 2122.72   268.9  2118.5
   283.2 2114.84   290.1 2113.96   300.72114.849   306.6  2115.8     310 2117.46
   313.3  2119.6   321.1 2127.23   326.5  2129.6   372.3 2136.38   408.9 2137.19
   418.7 2138.16   425.3 2140.32   444.9 2143.96   458.3  2145.5   486.9 2151.97
#Mann= 3 ,-1 , 0
       0      .1       0   283.2    .045       0   300.7      .1       0
Bank Sta=283.2,300.7
XS Rating Curve= 0 ,0
Exp/Cntr(USF)=0,0
Exp/Cntr=0.3,0.1

Type RM Length L Ch R = 1 ,15943   ,122.1,126.2,129.2
XS GIS Cut Line= 4
2037315.93361994261657.6952945992037172.89963569261553.016792157
2037011.48698307261538.6334864782036873.33802558261530.862607619
#Sta/Elev= 30
       0 2180.57    13.1 2175.45      36 2162.66    90.8 2137.05   101.9 2133.61
   121.4 2133.05     132 2129.64   153.9  2114.4   157.8 2113.61   201.2 2114.87
   214.3 2113.15   240.7 2113.93   249.22108.667   253.9  2107.9   272.12108.678
   286.8 2111.53   296.7 2110.69   309.9 2112.61   313.1 2114.29   319.7 2120.83
   326.3 2123.71   342.9 2126.17   382.2 2128.97   388.8 2131.05   408.5 2131.07
   415.1 2135.65   424.9 2140.01   443.8 2144.77   457.8 2150.67   477.7 2156.67
#Mann= 3 ,-1 , 0
       0      .1       0   249.2    .045       0   272.1      .1       0
#XS Ineff= 2 , 0
             241    2115     290            2115
Permanent Ineff=
       F       F
Bank Sta=249.2,272.1
XS Rating Curve= 0 ,0
Exp/Cntr(USF)=0,0
Exp/Cntr=0.3,0.1