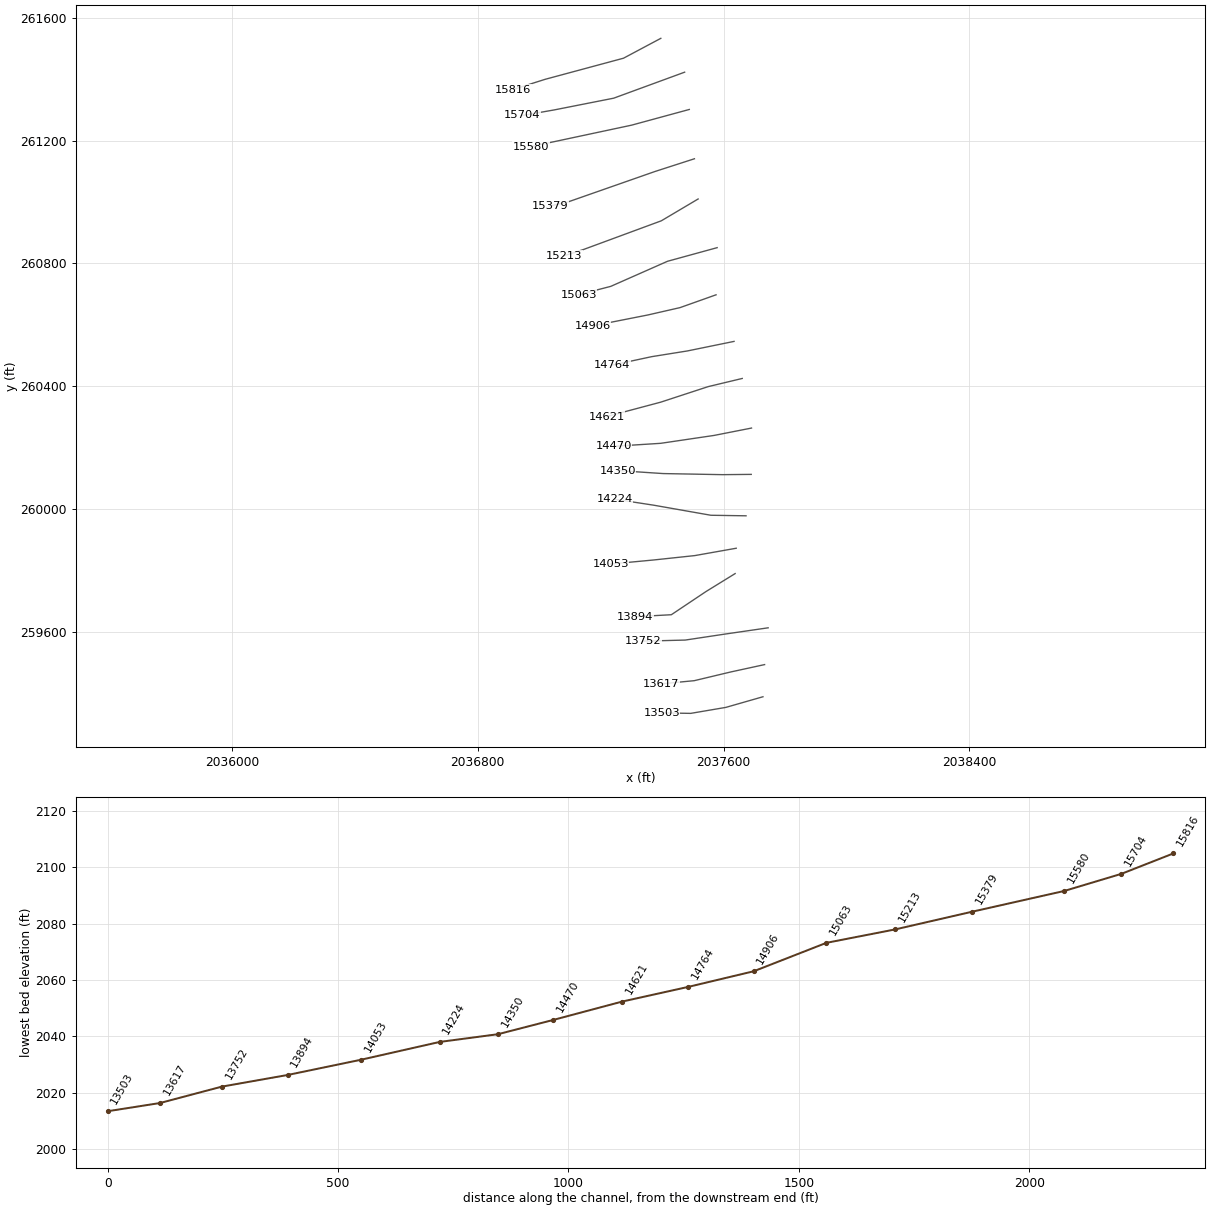
HEC-RAS study HNGRDCK_2.prj: HNGRDCK_2

--- HNGRDCK_2.g01 (geometry) --- (continued)

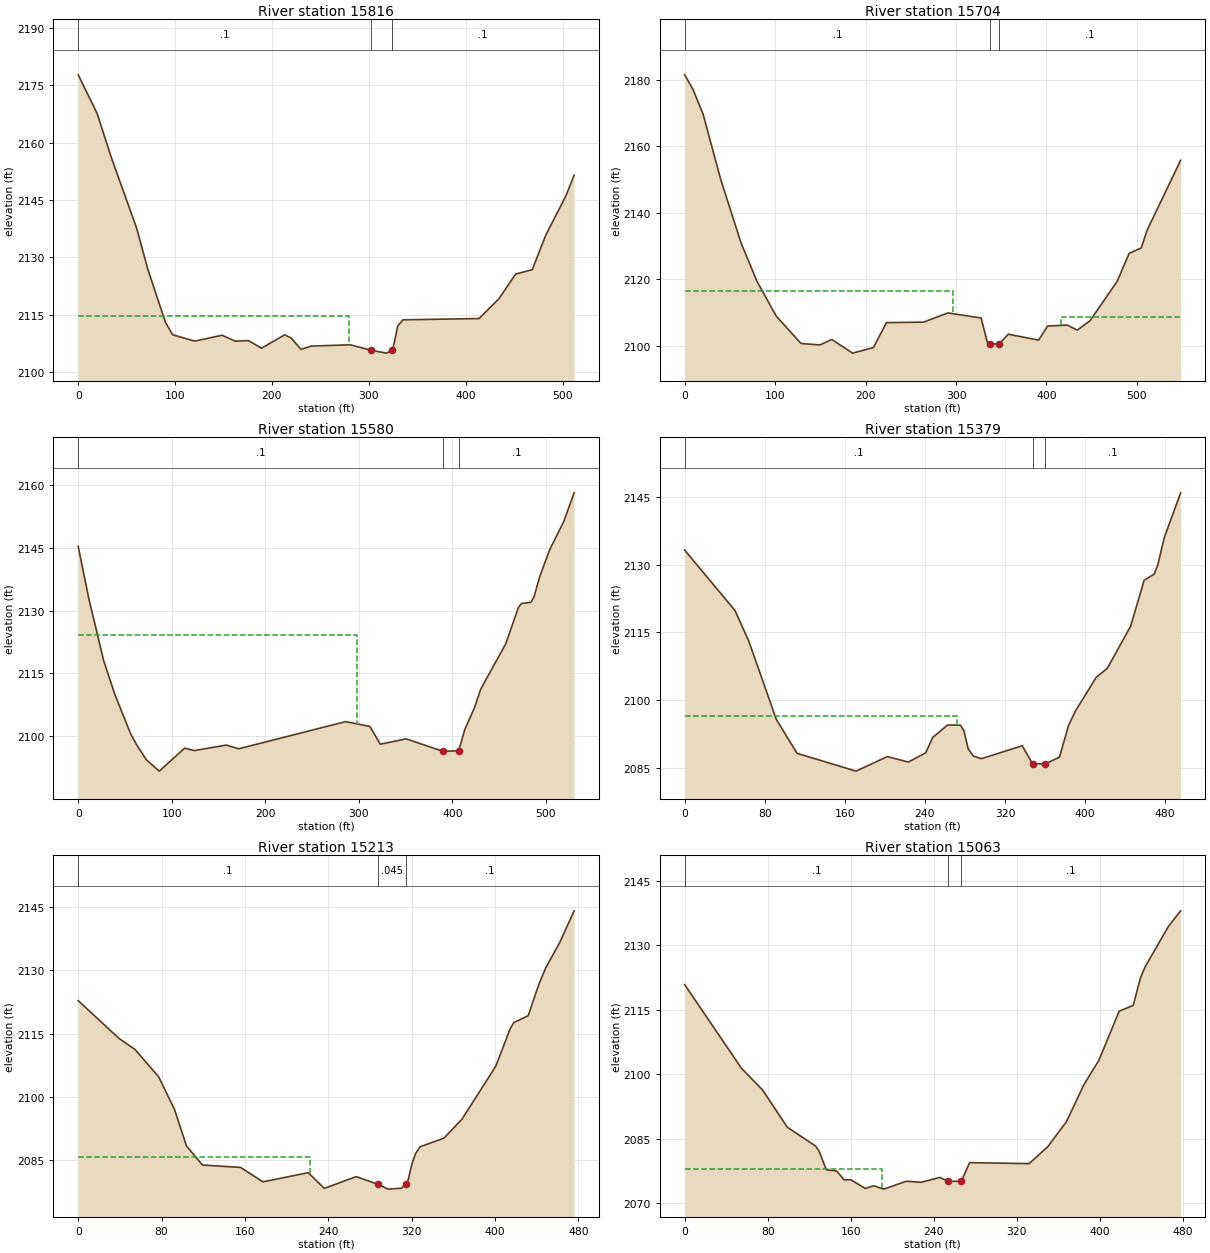
Type RM Length L Ch R = 1 ,15816   ,113.1,112.9,112.7
XS GIS Cut Line= 4
2037395.84087371261533.0399787142037274.38184798261468.315103158
2037019.47770844261399.5948649142036914.36988699261366.207674572
#Sta/Elev= 30
       0 2177.68    19.4 2167.68    34.2 2156.07    60.3 2137.65    72.2 2126.63
      90 2113.08    97.4 2109.81   120.2 2108.13   148.5 2109.67   162.1 2108.12
   175.7 2108.28   189.2 2106.28     213 2109.77   219.8 2108.95     230 2105.96
   240.2 2106.85     281 2107.17   302.12105.751   318.4    2105   323.52105.762
   325.2 2106.54   329.8 2112.08   335.2  2113.7   413.7 2114.03   434.3 2119.21
   451.5 2125.65   468.7  2126.8   482.5 2135.77   503.2 2145.97   511.9 2151.49
#Mann= 3 ,-1 , 0
       0      .1       0   302.1    .045       0   323.5      .1       0
#XS Ineff= 2 , 0
             280 2114.76
Permanent Ineff=
       T       F
Bank Sta=302.1,323.5
XS Rating Curve= 0 ,0
Exp/Cntr(USF)=0,0
Exp/Cntr=0.3,0.1

Type RM Length L Ch R = 1 ,15704   ,125.1,123.9,129.4
XS GIS Cut Line= 4
2037473.35090987261422.7679685082037242.41894647 261338.06627951
 2037048.2443198261299.7107976992036945.37371017261281.670056458
#Sta/Elev= 30
       0 2181.55     9.2 2177.16    20.4 2169.67    39.8 2150.09    62.3 2130.96
    79.8 2119.45   101.2 2108.89   128.7 2100.63   149.7 2100.22   162.6 2101.86
   185.6 2097.74   208.6 2099.41   223.1 2106.93   264.2 2107.08     291 2109.85
   327.7 2108.32   334.4  2101.2   337.8 2100.52   347.8 2100.54   357.8 2103.44
   391.3 2101.66   401.3  2105.9     423 2106.19   434.1 2104.67   448.1 2107.48
   478.1 2119.34   491.4  2127.8   504.7 2129.39   511.4 2134.85   548.3  2155.8
#Mann= 3 ,-1 , 0
       0      .1       0   337.8    .045       0   347.8      .1       0
#XS Ineff= 2 , 0
          297.19 2116.39  415.92         2108.61
Permanent Ineff=
       T       T
Bank Sta=337.8,347.8
XS Rating Curve= 0 ,0
Exp/Cntr(USF)=0,0
Exp/Cntr=0.3,0.1

Type RM Length L Ch R = 1 ,15580   ,199.5,200.6,203.1
XS GIS Cut Line= 4
2037488.53328809261301.3089427742037300.75124172 261250.16830036
2037001.09904008261186.2424973422036972.76184572261179.635379487
#Sta/Elev= 30
       0 2145.35    11.2    2133    27.2 2118.05      39 2110.08      56  2100.6
      62 2098.12    72.7 2094.41    86.6 2091.66   113.8 2097.15     124 2096.56
   158.2 2097.88   171.6    2097     286 2103.49   311.8 2102.32   322.9 2098.09
   350.5 2099.37     390 2096.38   406.7 2096.54   413.4 2101.71   423.5 2106.76
   430.2 2111.23   457.1 2122.13   470.5 2130.73   473.8 2131.69   483.9 2131.98
   487.2 2133.29   493.5 2138.26     504 2144.55   518.9 2151.23   530.1 2158.12
#Mann= 3 ,-1 , 0
       0      .1       0     390    .045       0   406.7      .1       0
#XS Ineff= 2 , 0
          297.92 2124.17
Permanent Ineff=
       T       F
Bank Sta=390,406.7
XS Rating Curve= 0 ,0
Exp/Cntr(USF)=0,0
Exp/Cntr=0.3,0.1

Type RM Length L Ch R = 1 ,15379   ,165.6,166.2,164.2
XS GIS Cut Line= 4
2037505.31381138261140.6953626922037376.66313281 261099.14359073
2037093.79145445261000.0585960522037034.73619835 260986.81750724
#Sta/Elev= 30
       0 2133.23    50.3 2119.84    64.1 2113.02    91.6 2095.69   112.3  2088.2
   171.2 2084.26   202.5 2087.48   223.4 2086.27   240.8 2088.32   247.7  2091.7
   262.6 2094.48   275.5 2094.44     279 2093.15   283.2 2089.21   288.3  2087.6
   296.4 2087.01   337.2 2089.89   347.5  2085.9   360.4 2085.86   374.4 2087.37
   383.3 2094.29   390.2 2097.53   411.1 2105.05   422.2 2107.04   445.5  2116.4
     459 2126.56     469 2127.91   472.4  2129.8   479.1 2136.01   495.4 2145.92
#Mann= 3 ,-1 , 0
       0      .1       0   347.5    .045       0   360.4      .1       0
#XS Ineff= 2 , 0
           271.7 2096.39
Permanent Ineff=
       T       F
Bank Sta=347.5,360.4
XS Rating Curve= 0 ,0
Exp/Cntr(USF)=0,0
Exp/Cntr=0.3,0.1

Type RM Length L Ch R = 1 ,15213   ,145.2,149.6,152.3
XS GIS Cut Line= 4
2037517.29989945261009.6474665052037397.43901879260938.530010648
2037144.13302433260845.0385237342037080.82071436260824.555129332
#Sta/Elev= 30
       0 2122.82      39 2113.87    54.3 2111.26    77.2 2104.72    92.4 2096.96
   103.9 2088.27   119.2 2083.73   155.8 2083.17   177.3 2079.73   220.7 2081.91
   236.2 2078.18   266.7 2080.97   287.92079.143   297.4    2078   310.1 2078.22
   314.3 2079.14   316.7 2080.29   320.3 2084.08   323.7 2086.43     328 2088.07
     351 2090.13   368.2 2094.61   400.6  2107.2   414.5 2116.13     418 2117.61
   431.8 2119.25   442.1 2126.75   448.8  2130.7   461.9 2136.58   475.9 2144.18
#Mann= 3 ,-1 , 0
       0      .1       0   287.9    .045       0   314.3      .1       0
#XS Ineff= 2 , 0
          222.64 2085.59
Permanent Ineff=
       F       F
Bank Sta=287.9,314.3
XS Rating Curve= 0 ,0
Exp/Cntr(USF)=0,0
Exp/Cntr=0.3,0.1

Type RM Length L Ch R = 1 ,15063   ,166.5,157.7,156.6
XS GIS Cut Line= 4
2037579.21839476260851.0603985012037417.62817047260806.667479739
2037232.95362841260724.9845092162037127.89498492260697.696549869
#Sta/Elev= 30
       0  2120.8    54.8 2101.33    75.2 2096.26      99 2087.61   126.2 2083.25
   129.7 2082.01   136.5 2077.72   146.7 2077.42   153.7 2075.38   160.3 2075.39
   174.2 2073.37     182 2074.01     192 2073.22   213.7 2075.06     228 2074.81
     246 2075.95   254.2 2075.03   266.7 2075.06   274.7 2079.38   332.1 2079.16
     350 2083.09   367.9 2088.87     385 2097.58   399.3  2103.2   418.9 2114.64
   432.4 2115.97   439.2 2122.24   443.8 2124.91   466.3 2134.34   478.1 2137.98
#Mann= 3 ,-1 , 0
       0      .1       0   254.2    .045       0   266.7      .1       0
#XS Ineff= 2 , 0
             190    2078
Permanent Ineff=
       F       F
Bank Sta=254.2,266.7
XS Rating Curve= 0 ,0
Exp/Cntr(USF)=0,0
Exp/Cntr=0.3,0.1

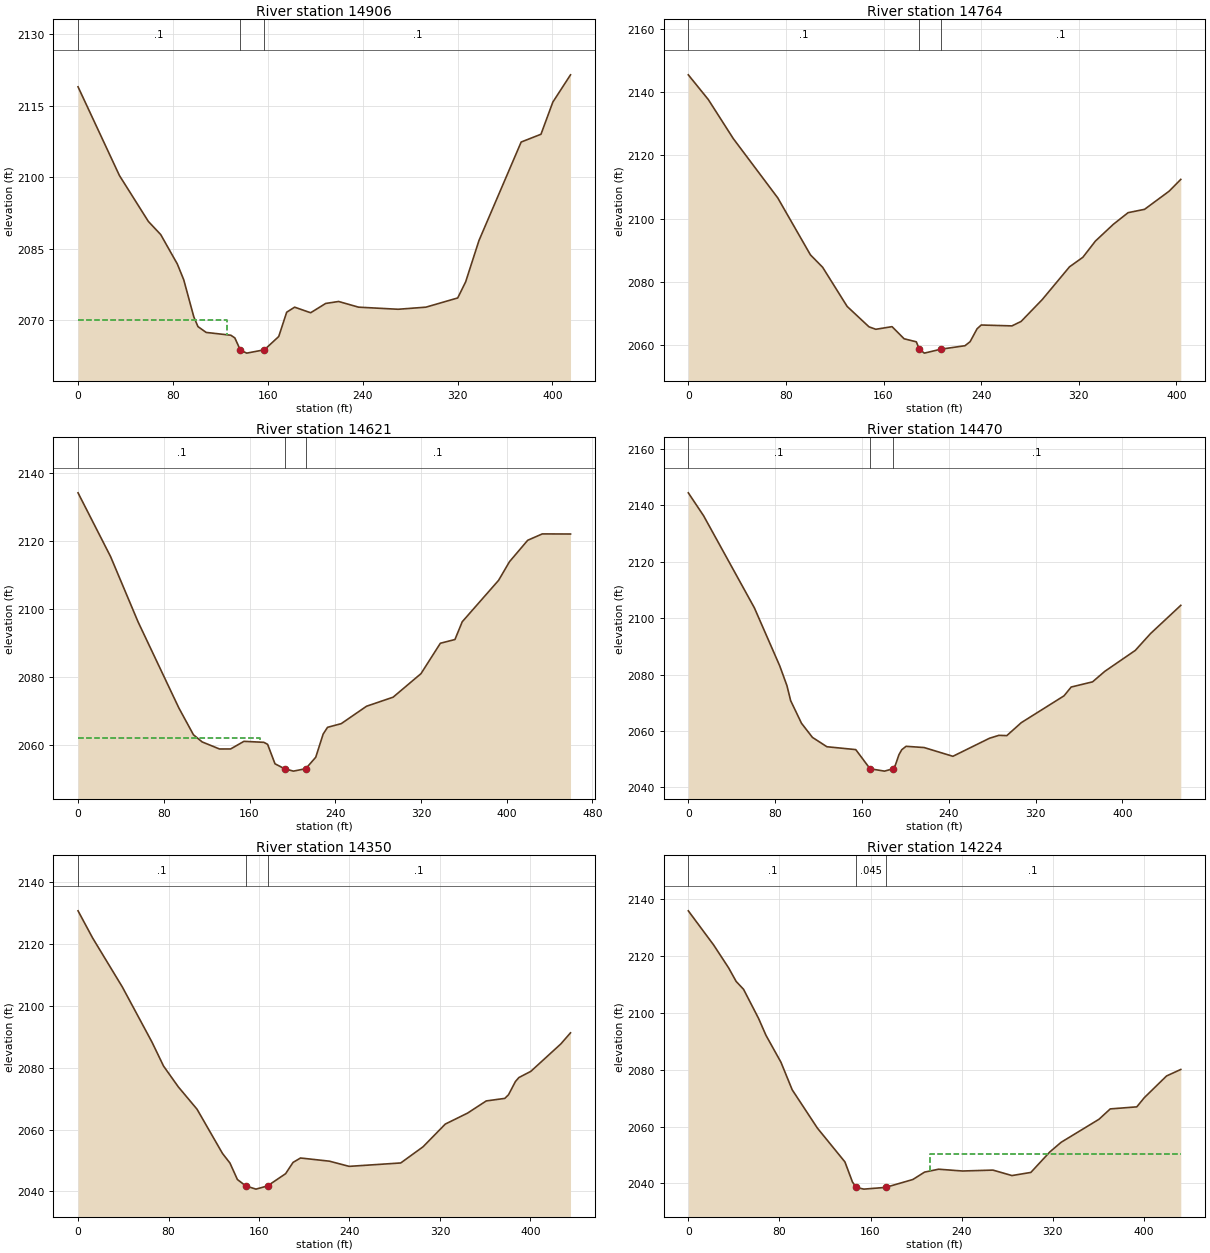
Type RM Length L Ch R = 1 ,14906   ,144.8,142,142
XS GIS Cut Line= 4
2037575.66696126260697.4608995832037458.46965573260655.731555947
2037353.70236745260631.7593798152037173.84884106260596.213107637
#Sta/Elev= 30
       0 2118.92    34.9 2100.33    59.3 2090.71    69.7 2087.96    83.7  2081.8
    89.1  2078.5    97.6 2070.73   101.1 2068.68     108 2067.46   128.8 2066.87
   132.2 2066.31   136.82063.775   142.2 2063.12   157.1 2063.82   169.2  2066.6
   175.9 2071.69   182.6 2072.75   196.1 2071.58   208.8 2073.53   219.7 2073.94
   236.5 2072.75   269.9 2072.31   293.3 2072.75   320.1 2074.68   326.8 2078.06
     338  2086.7   373.6 2107.35   390.3 2108.98   400.3 2115.72   415.2 2121.43
#Mann= 3 ,-1 , 0
       0      .1       0   136.8    .045       0   157.1      .1       0
#XS Ineff= 2 , 0
           125.4    2070
Permanent Ineff=
       F       F
Bank Sta=136.8,157.1
XS Rating Curve= 0 ,0
Exp/Cntr(USF)=0,0
Exp/Cntr=0.3,0.1

Type RM Length L Ch R = 1 ,14764   ,139.4,143,145.5
XS GIS Cut Line= 4
2037634.26561403260545.6371174162037482.44183186260514.562074282
 2037366.1323847260495.9170484022037238.14797479260468.420397834
#Sta/Elev= 30
       0 2145.46    16.4 2137.65    36.9  2125.3    73.3 2106.61   100.1 2088.61
   110.1 2084.69   130.2 2072.32   148.1 2065.88   153.7  2065.1     167 2065.93
   176.9  2062.1   186.9 2061.14   189.42058.792   193.5 2057.57     2072058.808
   226.8 2059.91     231 2061.18   236.7 2065.25   240.1 2066.45   265.3 2066.17
   272.8 2067.58   290.1 2074.47   312.5 2084.83   323.4 2087.83   333.7 2092.95
   348.4 2098.25   360.5 2101.93     374 2102.98   394.1  2108.7   403.7 2112.44
#Mann= 3 ,-1 , 0
       0      .1       0   189.4    .045       0     207      .1       0
Bank Sta=189.4,207
XS Rating Curve= 0 ,0
Exp/Cntr(USF)=0,0
Exp/Cntr=0.3,0.1

Type RM Length L Ch R = 1 ,14621   ,153.6,150.6,146.7
XS GIS Cut Line= 4
2037660.90136528260424.8883783822037549.91906838260398.252627125
2037395.43171108260347.6446997352037218.74789441260300.588205847
#Sta/Elev= 30
       0  2134.2    30.4 2115.43      56 2096.27    94.1 2070.93   107.7 2063.06
   115.8 2060.96     132 2058.88   142.4 2058.89   154.8 2061.13   173.4 2060.84
   176.9 2060.25   183.8 2054.52  192.692053.085     201 2052.37  212.482053.087
   221.8 2056.45   228.7 2063.25   232.8 2065.25   245.6 2066.33   269.2 2071.45
     294 2074.11     320 2081.03   338.1 2089.97   351.7 2091.07   358.5 2096.29
   392.4 2108.46   402.6 2113.95   419.6 2120.25   433.2 2122.12 459.542 2122.09
#Mann= 3 ,-1 , 0
       0      .1       0  192.69    .045       0  212.48      .1       0
#XS Ineff= 2 , 0
       0     170    2062               0
Permanent Ineff=
       F       F
Bank Sta=192.69,212.48
XS Rating Curve= 0 ,0
Exp/Cntr(USF)=0,0
Exp/Cntr=0.3,0.1

Type RM Length L Ch R = 1 ,14470   ,123.2,119.6,116.8
XS GIS Cut Line= 4
2037691.08855004260263.2981540872037569.45195263260239.325977955
2037395.43171108260213.5780850732037241.83221217260203.811642945
#Sta/Elev= 30
       0 2144.49    14.1 2136.35    60.9 2103.69    84.3 2083.07    90.9 2076.09
    94.3  2070.8   104.3 2062.77   114.4 2057.76   127.7 2054.45   154.3 2053.43
  167.492046.636   180.8  2045.8   188.52046.634   190.7 2047.83   194.1 2051.63
   196.7  2053.4   200.7  2054.6   217.3 2054.16   243.8 2051.06   277.6 2057.47
   286.2 2058.49   293.5  2058.4   306.8 2062.98   346.2  2072.5   352.8 2075.62
   372.5 2077.46   383.8 2081.19   411.9 2088.62   425.9 2094.57453.8008 2104.59
#Mann= 3 ,-1 , 0
       0      .1       0  167.49    .045       0   188.5      .1       0
Bank Sta=167.49,188.5
XS Rating Curve= 0 ,0
Exp/Cntr(USF)=0,0
Exp/Cntr=0.3,0.1

Type RM Length L Ch R = 1 ,14350   ,130.3,126.5,124.1
XS GIS Cut Line= 4
2037690.20069167260112.3622302942037596.08770389260111.474371919
2037403.42243646 260115.02580542 2037255.1500878260124.792247548
#Sta/Elev= 30
       0 2130.62    12.9 2121.85    39.2 2106.01    65.4 2088.21    75.6 2080.49
    88.6  2073.8   105.2 2066.56   127.7 2052.28   134.3 2049.18   140.9 2043.85
  148.342041.785   157.3 2040.75  167.522041.787   183.5 2045.73   190.1 2049.38
   196.7  2050.8   222.2 2049.78   239.7  2048.1   285.3  2049.2     305 2054.41
   324.7 2061.76   344.4  2065.3   360.9 2069.23   377.3 2070.05   380.6 2071.23
   386.7  2075.5   389.8 2076.79   400.3 2078.78   426.8 2087.62435.4088 2091.22
#Mann= 3 ,-1 , 0
       0      .1       0  148.34    .045       0  167.52      .1       0
Bank Sta=148.34,167.52
XS Rating Curve= 0 ,0
Exp/Cntr(USF)=0,0
Exp/Cntr=0.3,0.1

Type RM Length L Ch R = 1 ,14224   ,168.5,170.5,176.3
XS GIS Cut Line= 4
2037673.33138254259977.4077572572037558.79765213259979.183474007
2037372.34739333260012.0342338912037245.38364567260031.567118147
#Sta/Elev= 30
       0 2135.83    22.3 2123.79    35.4 2115.77      42 2111.01    48.5 2108.24
    61.7 2097.99    68.2 2092.05    81.3 2082.63    91.2 2072.92   113.3 2059.46
   137.5 2047.56   144.1  2040.5  147.432038.616   154.1    2038  173.262038.614
   197.1 2041.38   207.4 2043.98   219.7    2045   240.7 2044.37   267.4 2044.69
   284.1 2042.77   300.7 2043.87   317.3 2051.05   327.3 2054.47   360.5 2062.55
   370.4  2066.2   393.7 2066.92   400.3 2070.15   419.8 2077.77432.3271 2080.07
#Mann= 3 ,-1 , 0
       0      .1       0  147.43    .045       0  173.26      .1       0
#XS Ineff= 2 , 0
                          211.76         2050.48
Permanent Ineff=
       F       T
Bank Sta=147.43,173.26
XS Rating Curve= 0 ,0
Exp/Cntr(USF)=0,0
Exp/Cntr=0.3,0.1

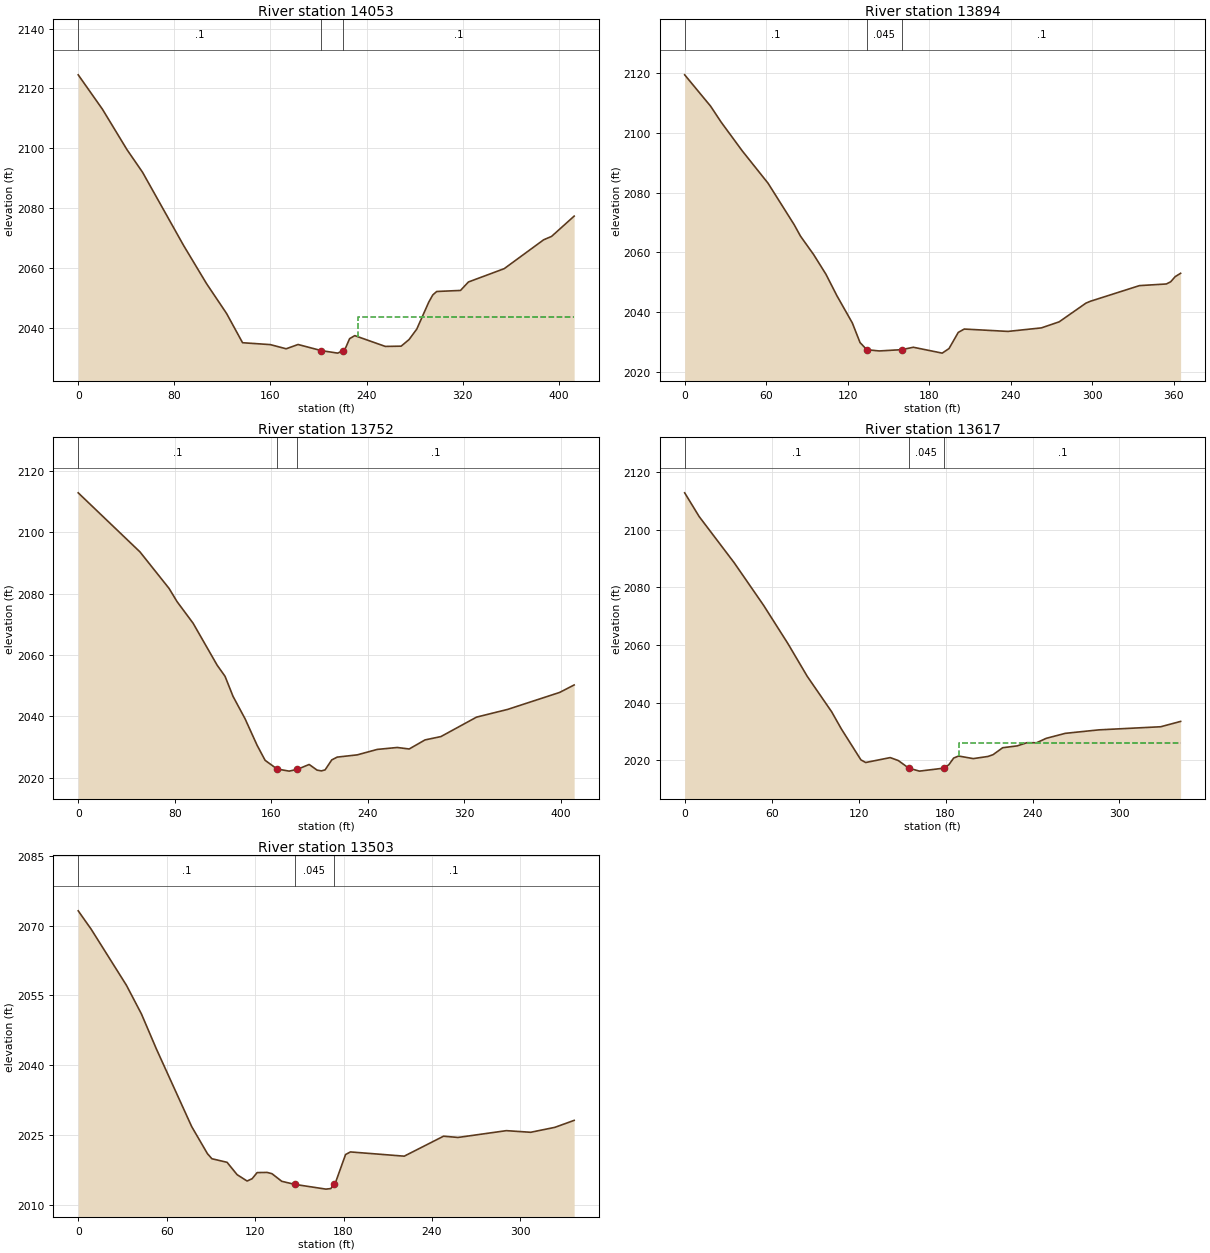
Type RM Length L Ch R = 1 ,14053   ,150.3,159.4,168.3
XS GIS Cut Line= 4
2037641.36848103259871.7526106022037506.41400799 259847.78043447
 2037373.2352517259833.5747004662037232.06577004259820.256824838
#Sta/Elev= 30
       0 2124.55    20.2 2113.05    40.7 2099.52    53.5 2092.07    87.8 2067.55
   106.8 2054.88   123.5 2044.91   136.8 2035.15   159.9 2034.52   173.1 2033.13
     183 2034.56  202.462032.508     216 2031.68  220.452032.508   222.6 2033.46
   225.9 2036.51   230.2 2037.52   255.6 2033.92   268.8    2034   275.4 2036.22
   281.8  2039.7   291.8 2048.71   295.1 2051.08   298.4 2052.25   318.2  2052.6
   324.8 2055.42   354.6 2059.87   387.4  2069.5     394 2070.63412.7976  2077.4
#Mann= 3 ,-1 , 0
       0      .1       0  202.46    .045       0  220.45      .1       0
#XS Ineff= 2 , 0
                          232.57         2043.57
Permanent Ineff=
       F       F
Bank Sta=202.46,220.45
XS Rating Curve= 0 ,0
Exp/Cntr(USF)=0,0
Exp/Cntr=0.3,0.1

Type RM Length L Ch R = 1 ,13894   ,152.9,142.6,136.1
XS GIS Cut Line= 4
2037637.81704753259789.1817817042037542.81620138259730.583128938
2037430.05818772259655.1151670412037312.41767018259648.769412983
#Sta/Elev= 30
       0 2119.55    19.1 2109.03    26.9 2103.66    42.4 2094.05    61.4  2083.2
    80.6 2069.32    85.3 2065.45    94.9 2059.32     104  2052.7   112.1 2045.48
   123.4  2036.4   129.1  2029.8   134.12027.405   143.2 2026.99   159.92027.423
   168.3 2028.23   189.6 2026.26   194.6 2027.79   201.4  2033.2   205.8 2034.33
     238 2033.54   262.6 2034.72   275.7 2036.75   295.4 2043.02   298.7 2043.65
   334.8 2048.89   354.6 2049.44   357.8 2050.18   361.1  2051.9   365.1 2053.02
#Mann= 3 ,-1 , 0
       0      .1       0   134.1    .045       0   159.9      .1       0
Bank Sta=134.1,159.9
XS Rating Curve= 0 ,0
Exp/Cntr(USF)=0,0
Exp/Cntr=0.3,0.1

Type RM Length L Ch R = 1 ,13752   ,131.3,134.6,136.8
XS GIS Cut Line= 4
2037745.24791093259612.4979650292037604.96628764259592.077222399
2037475.33896486259572.5443381432037337.19608583 259569.02797395
#Sta/Elev= 30
       0 2112.89    51.2 2093.62    75.3 2081.71    81.9 2077.42    95.2 2070.37
   115.1 2056.71   121.7 2053.04   128.3 2046.52   138.3 2039.19   148.2  2030.6
   154.9 2025.65   164.8 2022.83   174.8 2022.13   181.6 2022.71   191.4  2024.3
     198 2022.45   201.5 2022.21   204.6 2022.53   210.1 2025.78   214.6  2026.7
   231.2 2027.43   247.8 2029.21   264.4 2029.84   274.3 2029.35   287.4 2032.31
   300.6  2033.4   330.1 2039.74   355.9 2042.26     399  2047.8     411 2050.23
#Mann= 3 ,-1 , 0
       0      .1       0   164.8    .045       0   181.6      .1       0
Bank Sta=164.8,181.6
XS Rating Curve= 0 ,0
Exp/Cntr(USF)=0,0
Exp/Cntr=0.3,0.1

Type RM Length L Ch R = 1 ,13617   ,112.8,113.4,110.9
XS GIS Cut Line= 4
2037733.70575205259492.6370843712037623.61131352259468.664908239
2037504.63829124259440.2534402312037397.90467636259429.970135143
#Sta/Elev= 30
       0 2112.79      10 2104.56    34.2 2088.52    54.4 2073.82    71.2 2060.54
    84.6 2049.14   101.4 2036.88   108.1 2030.93   121.6  2020.2   124.9 2019.28
   141.8 2020.98   147.4 2019.96   154.62017.335     162 2016.29   178.9 2017.33
   182.3 2018.52   185.6 2020.82     189 2021.53   199.1 2020.63   209.3 2021.38
   212.8    2022   219.4  2024.4   229.5 2025.05   236.2 2026.15   242.8 2026.12
   249.4 2027.65   262.6 2029.39   285.6 2030.59   328.5 2031.68   342.2 2033.53
#Mann= 3 ,-1 , 0
       0      .1       0   154.6    .045       0   178.9      .1       0
#XS Ineff= 2 , 0
                          189.18         2025.95
Permanent Ineff=
       F       T
Bank Sta=154.6,178.9
XS Rating Curve= 0 ,0
Exp/Cntr(USF)=0,0
Exp/Cntr=0.3,0.1

Type RM Length L Ch R = 1 ,13503   ,128.8,126.6,124.8
XS GIS Cut Line= 4
 2037728.3786018259387.8697960922037607.62986277259353.243319457
2037493.09613236259333.7104352012037398.36735525259335.294528464
#Sta/Elev= 30
       0 2073.16     8.8 2069.21    32.7 2057.18    42.9 2051.01    53.1 2043.45
      77 2026.81    87.7 2020.99    90.7 2019.91     101 2019.14   107.8 2016.49
   114.6 2015.12     118 2015.62   121.4 2016.93   128.2 2016.97   131.5 2016.69
   138.1 2015.06   146.92014.403   168.1 2013.38   171.4  2013.5   173.5 2014.42
   174.8 2014.99   181.4 2020.81   184.7 2021.37   221.2 2020.46   247.9 2024.75
   257.7 2024.48   290.5 2025.94     307 2025.59   323.4 2026.65   336.5 2028.15
#Mann= 3 ,-1 , 0
       0      .1       0   146.9    .045       0   173.5      .1       0
Bank Sta=146.9,173.5
XS Rating Curve= 0 ,0
Exp/Cntr(USF)=0,0
Exp/Cntr=0.3,0.1