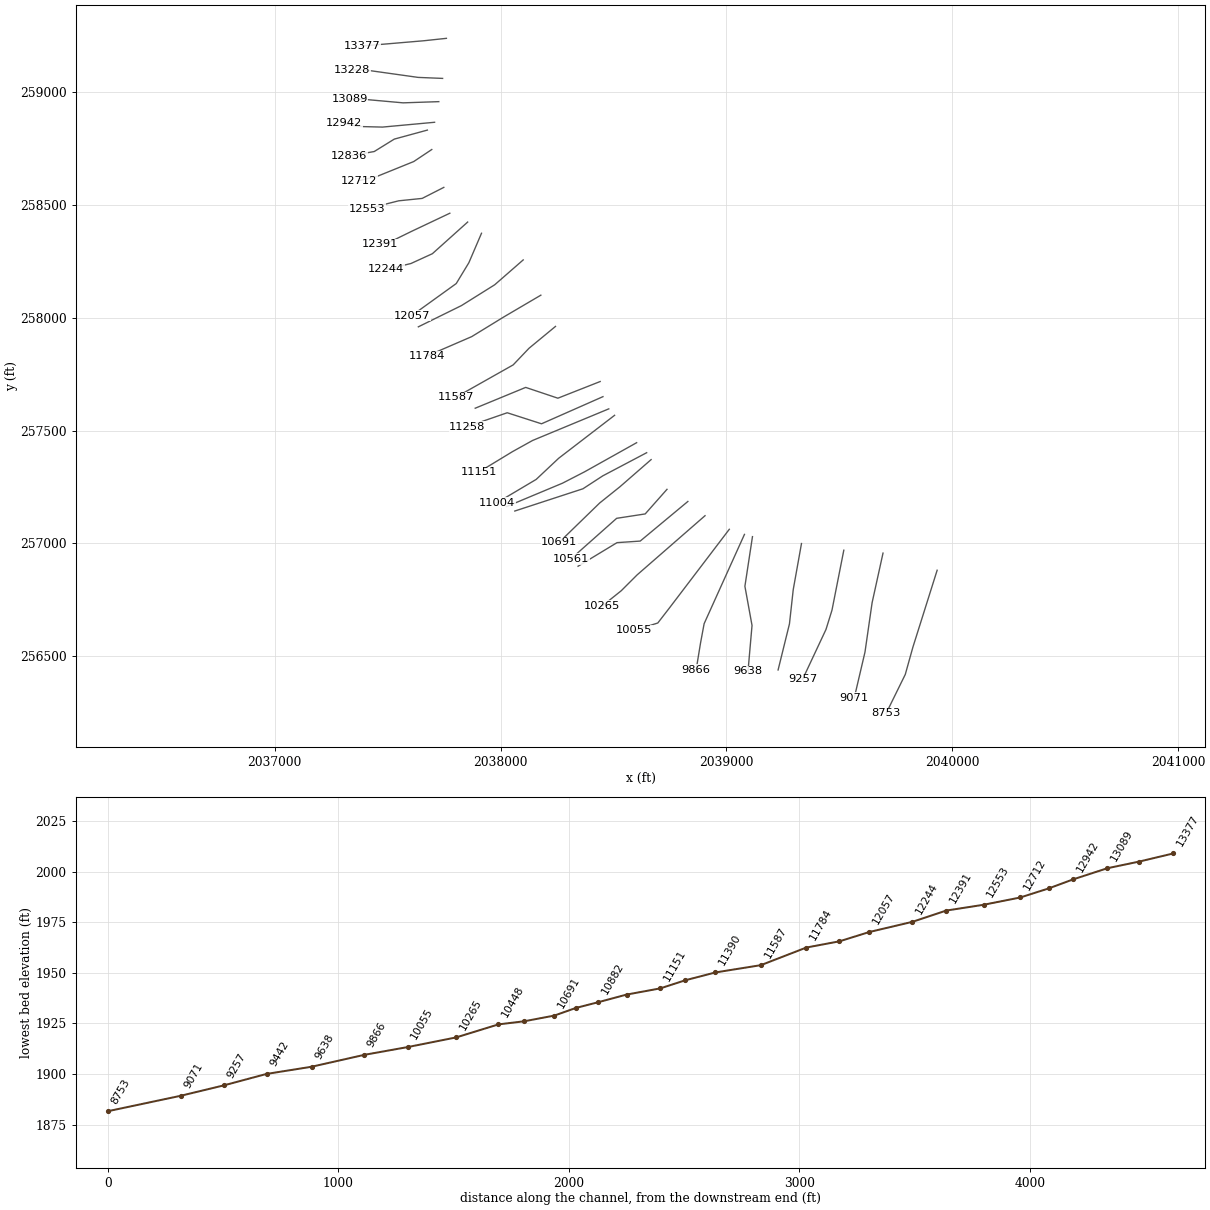
HEC-RAS study HNGRDCK_2.prj: HNGRDCK_2

--- HNGRDCK_2.g01 (geometry) --- (continued)

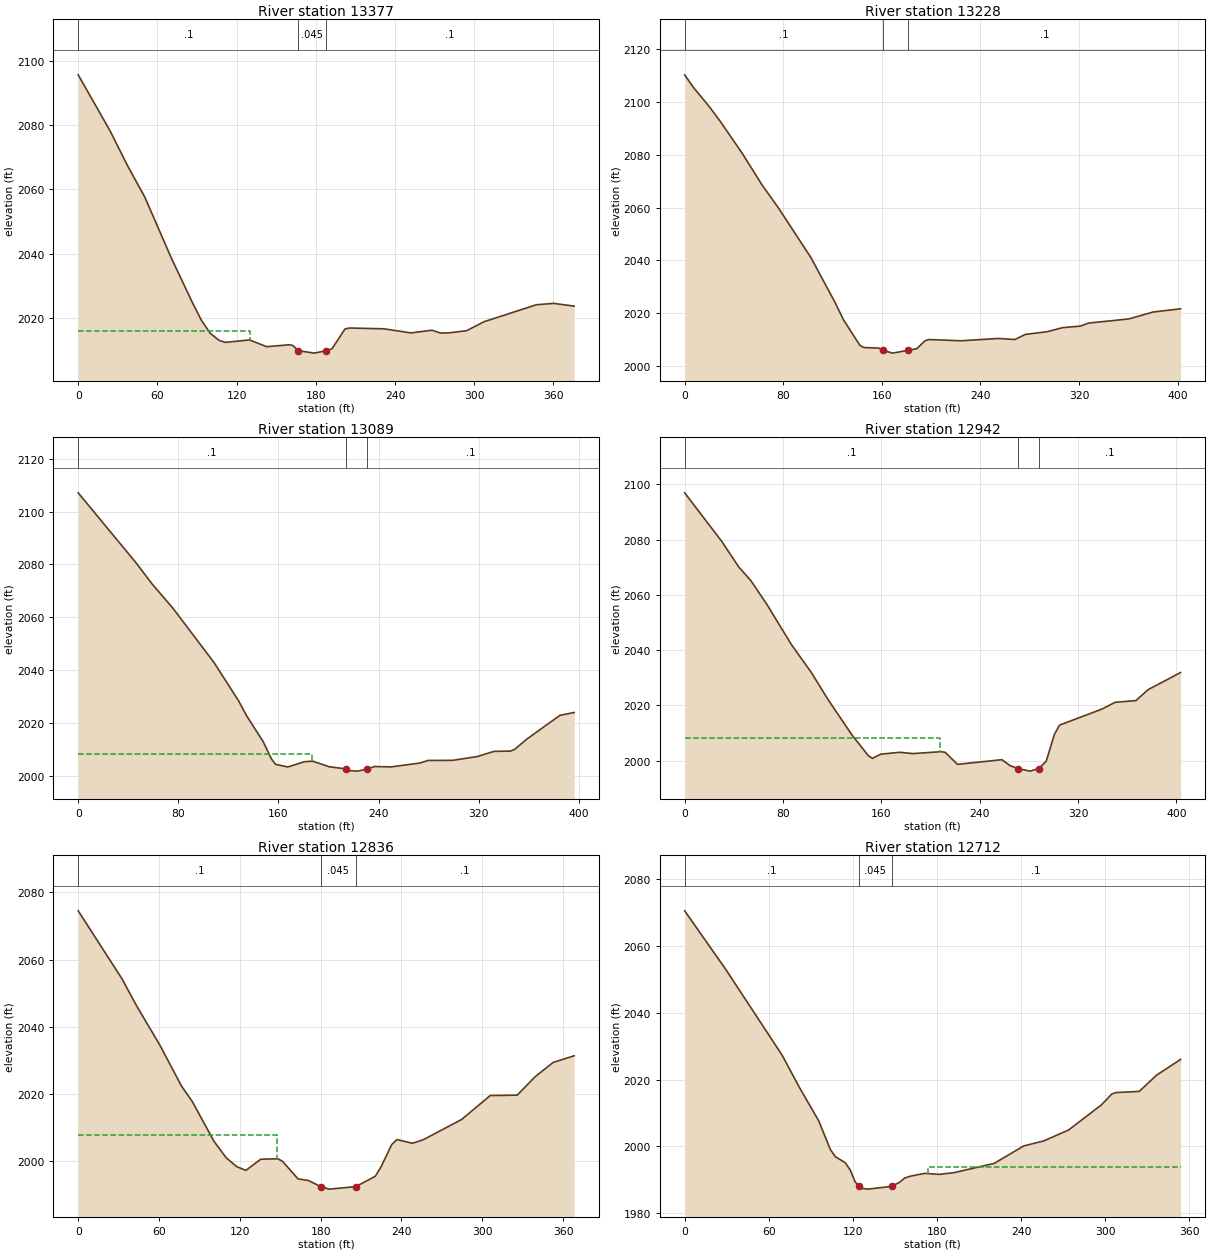
Type RM Length L Ch R = 1 ,13377   ,152.7,148.4,143.6
XS GIS Cut Line= 4
2037760.34150331 259238.709589052037660.90136528259228.055288547
2037484.21754861259212.9616961682037386.23112578259204.863644694
#Sta/Elev= 30
       0  2095.6    24.1 2078.19    37.3  2067.4    50.5 2057.52    70.3 2038.82
    86.8  2024.5    93.4 2019.18     100 2015.19   106.6 2013.03   111.5 2012.36
   129.7 2013.13   142.8 2011.02   160.1 2011.63   162.6 2011.39   166.82009.784
     179 2009.02   187.62009.781   192.2 2010.35   202.1 2016.52   205.4 2016.84
   231.7 2016.58     252 2015.31     268 2016.14   274.5 2015.26   281.1 2015.33
   294.3    2016   307.5  2018.8     347 2024.06   360.1  2024.5   375.7 2023.64
#Mann= 3 ,-1 , 0
       0      .1       0   166.8    .045       0   187.6      .1       0
#XS Ineff= 2 , 0
             130    2016
Permanent Ineff=
       F       F
Bank Sta=166.8,187.6
XS Rating Curve= 0 ,0
Exp/Cntr(USF)=0,0
Exp/Cntr=0.3,0.1

Type RM Length L Ch R = 1 ,13228   ,137.9,139.2,138.2
XS GIS Cut Line= 4
2037743.47219418   259061.137914 2037635.1534724259065.577205876
2037401.64671971 259098.427965762037343.37803322259098.638322029
#Sta/Elev= 30
       0 2110.14     7.1 2105.39    20.3 2097.94    29.2 2092.35    46.5 2080.64
    62.9 2068.46    76.1 2059.85   102.4 2041.14   122.2    2024   128.8 2017.65
   142.1 2007.99   145.4 2007.11   157.4 2006.89   161.22006.052   168.6 2004.99
   181.52006.055   188.4 2006.67   195.1 2009.66   198.4 2010.13   224.3 2009.66
   254.7 2010.53     268 2010.13   276.5 2012.06     294 2013.07   306.7 2014.61
     321 2015.19   327.6 2016.33   360.6 2017.92   380.2 2020.52   402.5 2021.74
#Mann= 3 ,-1 , 0
       0      .1       0   161.2    .045       0   181.5      .1       0
Bank Sta=161.2,181.5
XS Rating Curve= 0 ,0
Exp/Cntr(USF)=0,0
Exp/Cntr=0.3,0.1

Type RM Length L Ch R = 1 ,13089   ,138.8,147.4,145.9
XS GIS Cut Line= 4
2037726.60288505258958.1463424712037568.56409426 258952.81919222
2037410.52530346258967.0249262242037331.22139856258971.530829911
#Sta/Elev= 30
       0 2107.11    46.1 2080.65    59.2 2072.48    75.6 2063.43   108.4 2042.88
   128.1 2028.33   134.7 2022.52   147.8 2012.81   154.4 2006.28   157.7 2004.24
   167.5 2003.25   180.7 2005.22   187.3 2005.45   200.5 2003.34   213.82002.509
     217 2001.84   223.5 2001.67   231.12002.517   236.7 2003.41   249.9 2003.27
     273 2004.73   279.5 2005.72   299.3 2005.76   319.1 2007.22   332.2 2009.16
   345.4 2009.26   348.6 2009.89   358.6 2013.88   384.8 2022.79   396.2 2023.89
#Mann= 3 ,-1 , 0
       0      .1       0   213.8    .045       0   231.1      .1       0
#XS Ineff= 2 , 0
          186.68 2008.33
Permanent Ineff=
       T       F
Bank Sta=213.8,231.1
XS Rating Curve= 0 ,0
Exp/Cntr(USF)=0,0
Exp/Cntr=0.3,0.1

Type RM Length L Ch R = 1 ,12942   ,96.1,105.8,112.3
XS GIS Cut Line= 4
2037707.95785917258866.6969298212037477.11468161258845.388328815
 2037369.6838182 258848.051903942037307.06327347258861.839913789
#Sta/Elev= 30
       0 2096.92    30.2 2079.33      44 2070.08    53.9 2065.11      67 2056.45
    86.8 2042.03   103.3 2031.72   116.5 2022.18   136.2 2009.21   149.4 2001.79
   152.7 2000.81   159.3 2002.32   174.9 2003.02   185.6 2002.54   208.7 2003.24
     212 2002.97   221.9 1998.65     258 2000.34   264.6 1998.22     2711997.123
     281  1996.2     2881997.109   294.1 1999.82   300.7 2009.44   304.9 2012.85
   339.3 2018.64   350.2 2021.12     367 2021.72     377 2025.69   403.4 2031.89
#Mann= 3 ,-1 , 0
       0      .1       0     271    .045       0     288      .1       0
#XS Ineff= 2 , 0
          207.91  2008.1
Permanent Ineff=
       T       F
Bank Sta=271,288
XS Rating Curve= 0 ,0
Exp/Cntr(USF)=0,0
Exp/Cntr=0.3,0.1

Type RM Length L Ch R = 1 ,12836   ,129.2,123.9,122.4
XS GIS Cut Line= 4
2037675.99495766258832.0704531862037529.49832575  258792.1168263
2037440.71248822258737.0696070342037330.56481348258717.560055788
#Sta/Elev= 30
       0 2074.53    32.7 2054.17    42.9 2046.58    60.7 2034.52    76.7  2022.4
    84.7  2017.8   100.7 2006.04   109.9 2001.05   117.7 1998.43   124.5 1997.31
   135.5 2000.64   148.3 2000.75   151.7 2000.01   163.2 1994.79     171  1994.3
   180.1 1992.47   186.4 1991.74     2061992.475   220.6 1995.57     225  1998.5
   232.7 2004.96   236.6 2006.49   248.2 2005.38   256.3 2006.46   284.7 2012.47
   305.9 2019.58   325.9  2019.7   339.2 2025.17   352.6 2029.43   368.2 2031.41
#Mann= 3 ,-1 , 0
       0      .1       0   180.1    .045       0     206      .1       0
#XS Ineff= 2 , 0
          147.35 2007.98
Permanent Ineff=
       T       F
Bank Sta=180.1,206
XS Rating Curve= 0 ,0
Exp/Cntr(USF)=0,0
Exp/Cntr=0.3,0.1

Type RM Length L Ch R = 1 ,12712   ,165.6,159.2,154.1
XS GIS Cut Line= 4
2037695.52784192258745.9481907872037615.62058815258692.676688272
2037451.36678873258626.0873101282037372.99465966258608.105825971
#Sta/Elev= 30
       0 2070.41    29.4 2052.85    69.6  2027.2    81.9 2017.59    95.6 2007.65
   103.8 1999.18   107.4 1996.95   114.5 1995.14     118 1993.03   121.5 1989.48
   124.21988.054   125.8 1987.51   130.8 1987.24   147.6 1988.06   153.4 1989.31
   156.9 1990.56   161.1 1991.12   171.1 1991.94   181.7 1991.65   192.3 1992.18
   220.7 1994.93   241.9 2000.16   256.1 2001.65   273.7 2004.88   297.3 2012.45
   304.6 2015.66   307.4 2016.09   324.2 2016.45   336.6 2021.31   353.7 2026.01
#Mann= 3 ,-1 , 0
       0      .1       0   124.2    .045       0   147.6      .1       0
#XS Ineff= 2 , 0
                          173.31          1993.9
Permanent Ineff=
       F       F
Bank Sta=124.2,147.6
XS Rating Curve= 0 ,0
Exp/Cntr(USF)=0,0
Exp/Cntr=0.3,0.1

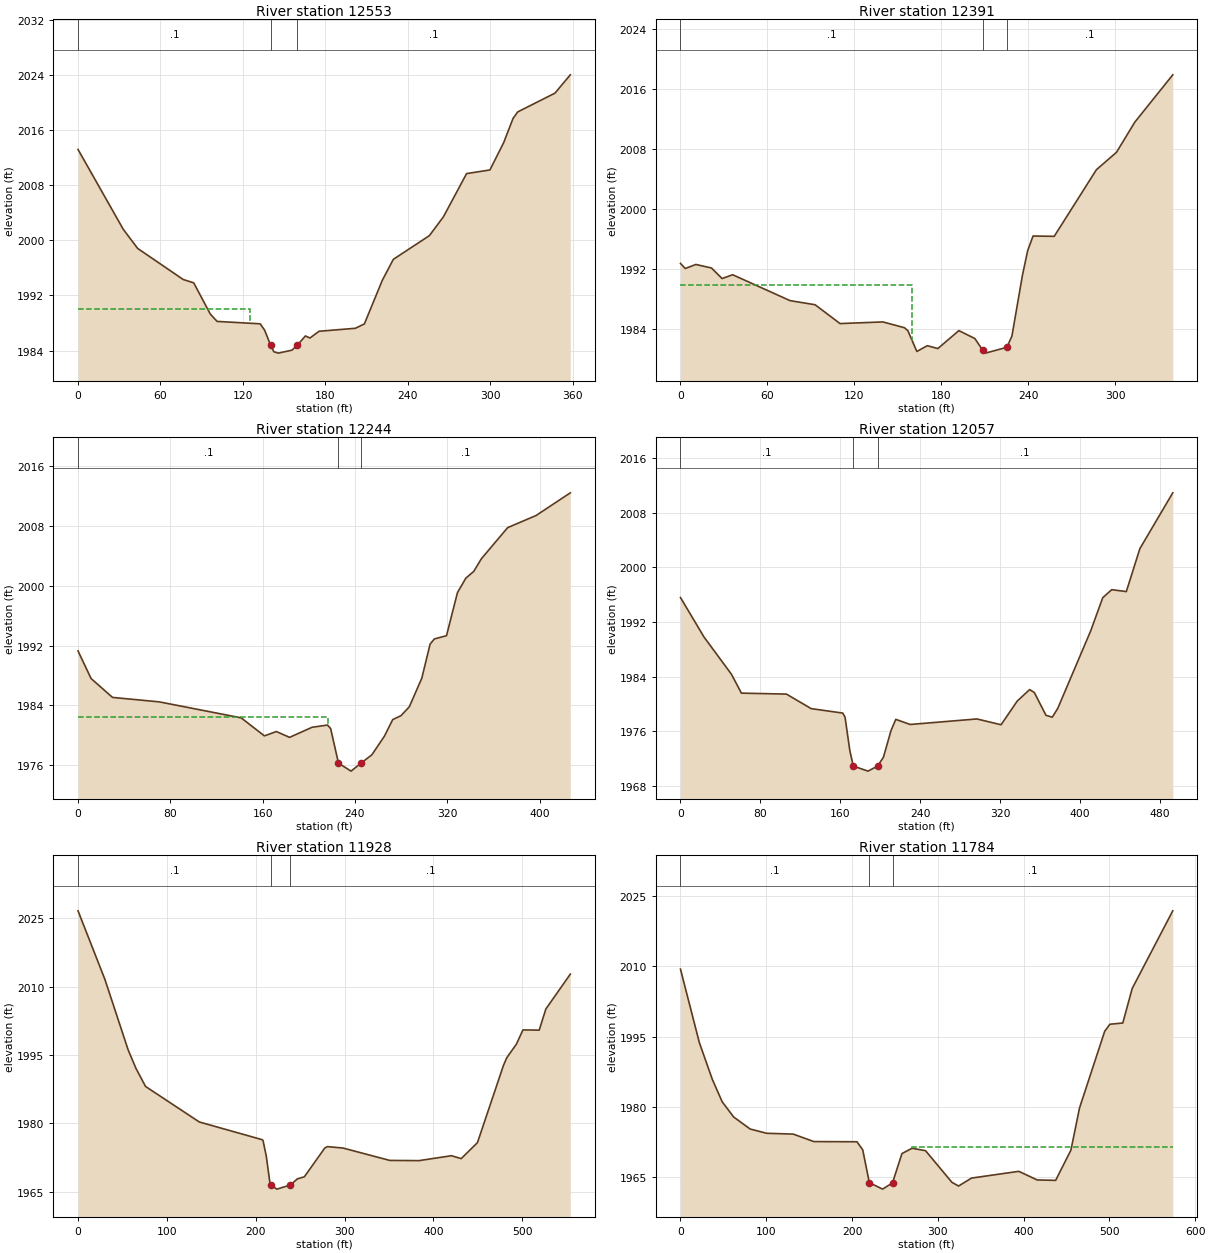
Type RM Length L Ch R = 1 ,12553   ,153.8,162.1,165.7
XS GIS Cut Line= 4
2037748.79934443258578.1429578652037652.91063991258529.310747226
   2037549.03121258518.656446723 2037407.2561758 258482.82319632
#Sta/Elev= 30
       0 2013.17    32.9  2001.6    43.4 1998.82    76.6 1994.31    84.2 1993.83
    96.3  1989.3   101.2 1988.24   132.6 1987.89   135.9 1986.94   140.2 1984.77
   142.5 1983.84   145.8 1983.64   155.7 1984.07   159.6 1984.79   165.5 1986.13
   168.8 1985.83   175.4 1986.81   201.8 1987.24   208.4 1987.87   221.4 1994.17
   229.5 1997.24   255.7 2000.67   265.9 2003.39   282.8 2009.67   299.8  2010.2
   309.8 2014.16   316.6 2017.66     320 2018.61   347.1 2021.33   358.3 2023.99
#Mann= 3 ,-1 , 0
       0      .1       0   140.2    .045       0   159.6      .1       0
#XS Ineff= 2 , 0
             125    1990
Permanent Ineff=
       F       F
Bank Sta=140.2,159.6
XS Rating Curve= 0 ,0
Exp/Cntr(USF)=0,0
Exp/Cntr=0.3,0.1

Type RM Length L Ch R = 1 ,12391   ,145.3,147.2,142.7
XS GIS Cut Line= 4
2037775.43509569258463.6092274582037604.96628764 258382.81411531
2037514.40473337258338.4211965482037466.03755058 258325.08631905
#Sta/Elev= 30
       0 1992.73     3.3 1992.05    10.6 1992.59    21.4 1992.12    28.7 1990.71
      36 1991.22    75.6 1987.77    92.9 1987.22   110.1 1984.71   139.7 1984.93
   154.5 1984.16   156.9 1983.77   163.1 1980.99   170.3 1981.76   177.6 1981.38
   192.1 1983.77   203.1 1982.72   208.6 1981.16   208.6 1981.14   210.4 1980.77
   225.21981.544   228.7 1983.03     236 1991.18   239.6 1994.45   243.3 1996.38
   257.9 1996.34     287 2005.22   300.9 2007.55   313.5 2011.56   339.7 2017.87
#Mann= 3 ,-1 , 0
       0      .1       0   208.6    .045       0   225.2      .1       0
#XS Ineff= 2 , 0
             160 1989.86
Permanent Ineff=
       T       F
Bank Sta=208.6,225.2
XS Rating Curve= 0 ,0
Exp/Cntr(USF)=0,0
Exp/Cntr=0.3,0.1

Type RM Length L Ch R = 1 ,12244   ,174.7,186.5,197.3
XS GIS Cut Line= 4
2037854.45449109258424.5434589472037698.19141704258284.261835657
2037603.19057089 258240.756775272037494.26585895258214.294839603
#Sta/Elev= 30
       0 1991.28    11.3 1987.59    29.9 1985.06    70.5 1984.46   141.4 1982.32
   161.5 1979.91   171.9 1980.49   183.3 1979.71   202.8 1981.06   216.2 1981.36
   218.9 1980.89   225.71976.261   236.6 1975.19   245.21976.259   254.6 1977.37
   265.5 1979.87   272.7 1982.09   279.9 1982.62   287.1 1983.81   297.9 1987.63
   305.1  1992.2   308.8 1992.89   319.3 1993.32   328.8 1999.09   336.1 2001.03
   342.9 2001.93   349.6 2003.64   372.3 2007.79   396.9 2009.41   426.6 2012.45
#Mann= 3 ,-1 , 0
       0      .1       0   225.7    .045       0   245.2      .1       0
#XS Ineff= 2 , 0
          216.44  1982.5
Permanent Ineff=
       T       F
Bank Sta=225.7,245.2
XS Rating Curve= 0 ,0
Exp/Cntr(USF)=0,0
Exp/Cntr=0.3,0.1

Type RM Length L Ch R = 1 ,12057   ,140.4,129.2,120.5
XS GIS Cut Line= 4
2037915.71671898258374.8233899332037859.78164134258244.308208771
 2037803.8465637258151.9709377452037606.74200439258009.913597706
#Sta/Elev= 30
       0  1995.6    23.5 1989.83      51 1984.37      61  1981.6   106.1 1981.46
   130.9 1979.33   162.5 1978.68   164.8 1978.08   169.6 1973.16  173.061970.922
   187.8 1970.18  197.361970.921   203.2 1972.21   210.8 1976.12   215.6 1977.76
     230 1977.01   296.8 1977.82     321 1976.97   337.2 1980.44   349.6 1982.12
   354.3 1981.69     366 1978.35   372.3 1978.08   377.8 1979.38   410.7  1990.7
   422.8 1995.57   431.8 1996.75   446.4 1996.47     460 2002.76492.9161 2010.93
#Mann= 3 ,-1 , 0
       0      .1       0  173.06    .045       0  197.36      .1       0
Bank Sta=173.06,197.36
XS Rating Curve= 0 ,0
Exp/Cntr(USF)=0,0
Exp/Cntr=0.3,0.1

Type RM Length L Ch R = 1 ,11928   ,144.1,144.1,144.7
XS GIS Cut Line= 4
2038100.39126103258256.7382260252037974.31537175258146.643787494
2037826.93088146258054.3065164682037636.04133078257960.193528692
#Sta/Elev= 30
       0 2026.63    30.3 2011.57    56.4 1996.14    65.2 1992.08      76 1988.11
   136.5 1980.32   207.2 1976.44   208.2 1976.28   211.9 1972.83   215.9 1967.12
   216.91966.503   223.8 1965.59  239.121966.503   246.9 1967.84   254.8  1968.3
   277.8 1974.62   280.9 1974.91   298.3  1974.6   350.8 1971.89   383.8 1971.84
   420.3 1972.92   431.3 1972.28   449.6 1975.79   478.9 1992.74   482.5 1994.38
   493.5 1997.41   500.8 2000.51   519.1 2000.46   526.6  2005.1554.1288 2012.74
#Mann= 3 ,-1 , 0
       0      .1       0   216.9    .045       0  239.12      .1       0
Bank Sta=216.9,239.12
XS Rating Curve= 0 ,0
Exp/Cntr(USF)=0,0
Exp/Cntr=0.3,0.1

Type RM Length L Ch R = 1 ,11784   ,190.4,197,200.9
XS GIS Cut Line= 4
2038178.52279805258100.4751519812038012.49328188258002.810730704
2037872.21165859257916.6884683042037673.33138254257830.566205905
#Sta/Elev= 30
       0 2009.37      22 1993.72    37.2 1985.85    48.6 1981.12      62 1977.87
    81.2 1975.31   100.4  1974.4   131.5 1974.22   155.5 1972.63   205.8 1972.59
   212.5 1970.86   220.2 1963.88   235.6  1962.5   247.2 1963.83   258.2 1970.07
     270 1971.21   285.7 1970.69   316.5 1963.95   324.2 1963.16   339.3 1964.85
   394.5 1966.29   415.9 1964.45   437.4 1964.37   455.2  1970.8   465.3 1979.82
   494.6 1996.13   500.7 1997.63   515.7 1997.89   526.7 2005.26573.9595 2021.79
#Mann= 3 ,-1 , 0
       0      .1       0   220.2    .045       0   247.2      .1       0
#XS Ineff= 2 , 0
                          269.87         1971.51
Permanent Ineff=
       F       F
Bank Sta=220.2,247.2
XS Rating Curve= 0 ,0
Exp/Cntr(USF)=0,0
Exp/Cntr=0.3,0.1

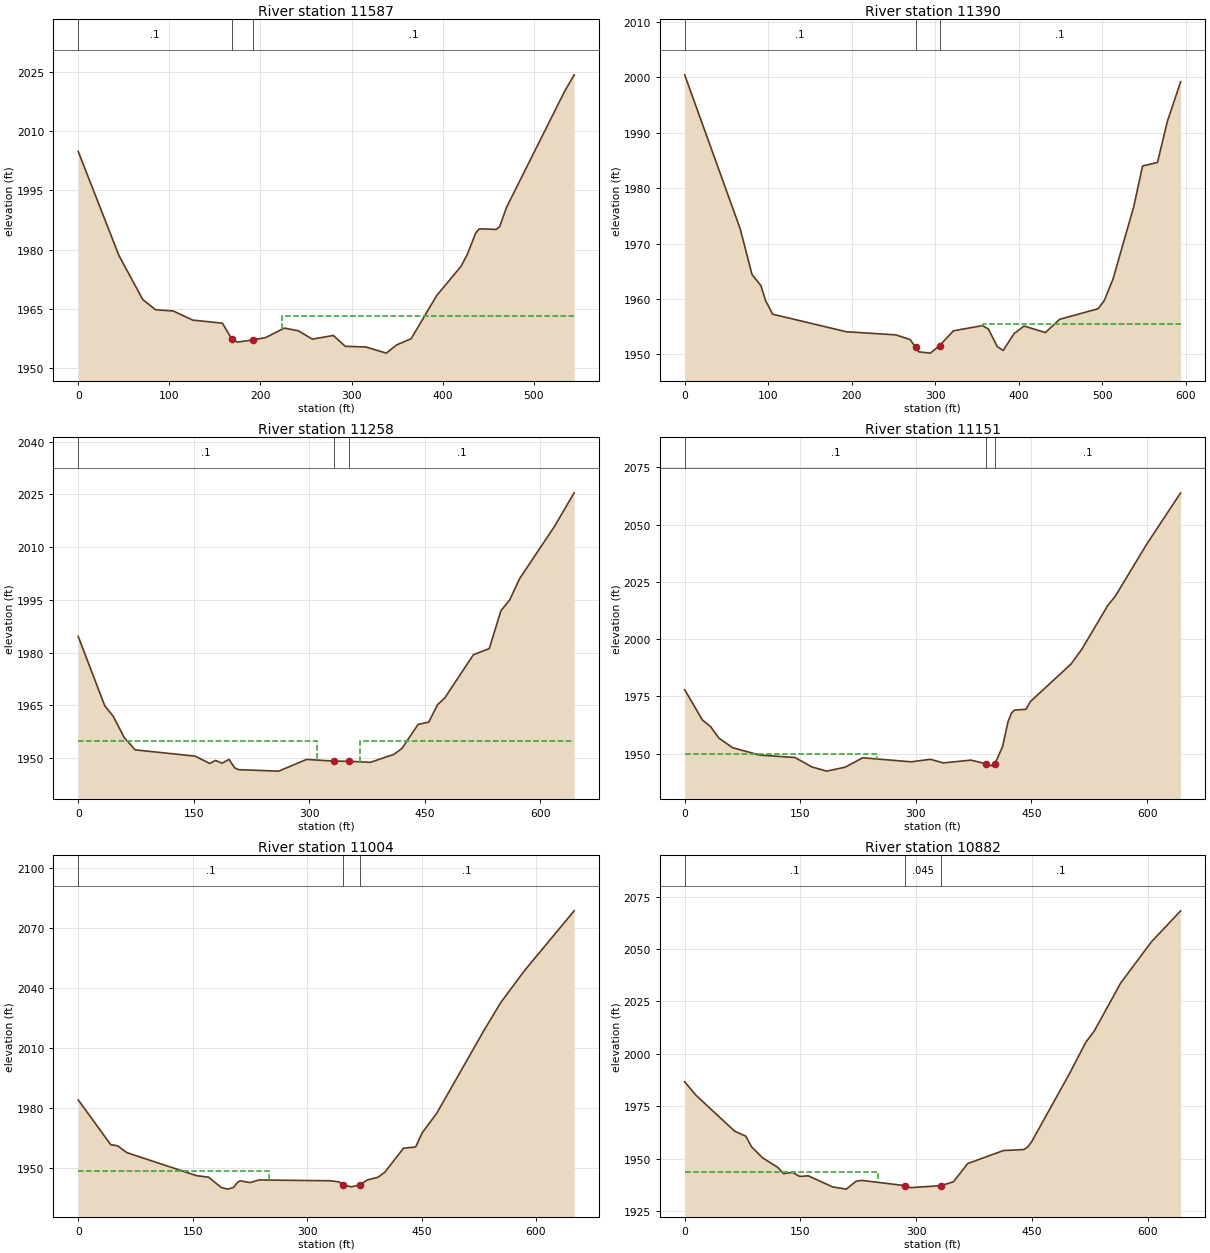
Type RM Length L Ch R = 1 ,11587   ,224.8,197.2,176.6
XS GIS Cut Line= 4
2038243.33645945257961.9692454422038126.13915391 257865.19268254
2038055.99834227257791.5004373942037802.95870532257648.555238979
#Sta/Elev= 30
       0 2004.85    44.8 1978.47    70.9 1967.36    84.9 1964.79   104.4 1964.47
   125.6 1962.17   158.3 1961.39   168.7 1957.31   174.9 1956.61   191.9 1957.15
   205.8 1957.75   226.2 1960.14   241.5 1959.48     257 1957.35     280 1958.28
   293.1 1955.54   315.6 1955.37   338.2 1953.81   349.5 1955.89   365.4 1957.45
   393.4 1968.36     420 1975.73   426.7 1978.58   436.2 1984.16     440 1985.26
   458.8 1985.13   462.6 1985.83   470.1 1990.69   533.4 2019.85544.3503 2024.25
#Mann= 3 ,-1 , 0
       0      .1       0   168.7    .045       0   191.9      .1       0
#XS Ineff= 2 , 0
                          223.99         1963.15
Permanent Ineff=
       F       F
Bank Sta=168.7,191.9
XS Rating Curve= 0 ,0
Exp/Cntr(USF)=0,0
Exp/Cntr=0.3,0.1

Type RM Length L Ch R = 1 ,11390   ,131.1,131.6,132.4
XS GIS Cut Line= 4
2038441.25370142257717.7804585992038253.91085243257643.908229589
2038111.39259034257691.7387919432037887.86828476257599.507889166
#Sta/Elev= 30
       0 2000.47    66.5 1972.63    80.6  1964.4    91.2 1962.41    96.9 1959.67
   105.3 1957.24   193.5 1954.07   252.7 1953.51   269.7 1952.66   276.41951.277
   280.1 1950.44     294 1950.21     305 1951.55   321.6 1954.24   356.4 1955.18
   363.5 1954.56   374.1 1951.38   381.2 1950.69     394 1953.71   406.1  1955.1
   431.7 1953.93   448.6 1956.31   494.8 1958.23   502.1  1959.7   512.5 1963.54
   537.2 1976.54     548 1984.02   565.8 1984.64   577.4 1991.94   593.5 1999.22
#Mann= 3 ,-1 , 0
       0      .1       0   276.4    .045       0     305      .1       0
#XS Ineff= 2 , 0
                          357.12         1955.39
Permanent Ineff=
       F       F
Bank Sta=276.4,305
XS Rating Curve= 0 ,0
Exp/Cntr(USF)=0,0
Exp/Cntr=0.3,0.1

Type RM Length L Ch R = 1 ,11258   ,96.5,107.6,122.1
XS GIS Cut Line= 4
2038453.61967324257650.7404755142038181.46142988257530.460802419
2038029.58285961257579.3881270682037853.24062702257518.228971257
#Sta/Elev= 30
       0 1984.62    34.5 1964.88    45.3 1961.96    59.6 1955.92      74 1952.35
   151.7 1950.58   170.8 1948.47   178.2 1949.36   186.9 1948.57   195.7 1949.67
   203.1 1947.25   208.1 1946.73   260.3 1946.31   296.4 1949.64   332.2 1949.15
     3511949.115   379.2 1948.81   410.2 1951.11   420.5 1952.85   441.2  1959.6
     455 1960.24   466.5 1965.21   475.8 1967.11     513 1979.41   533.6 1981.16
   548.7  1991.9   560.1 1994.98     573 2001.05   618.2 2015.88   643.8 2025.45
#Mann= 3 ,-1 , 0
       0      .1       0   332.2    .045       0     351      .1       0
#XS Ineff= 2 , 0
             310    1955   365.4            1955
Permanent Ineff=
       F       F
Bank Sta=332.2,351
XS Rating Curve= 0 ,0
Exp/Cntr(USF)=0,0
Exp/Cntr=0.3,0.1

Type RM Length L Ch R = 1 ,11151   ,144.6,146.5,150.2
XS GIS Cut Line= 4
2038479.40813633257596.6648494932038142.02195374257456.580528065
2038053.23611621257407.2550627732037902.30019242257315.509697331
#Sta/Elev= 30
       0 1977.92      23 1964.69    33.7 1961.76    44.3 1956.81    62.1 1952.58
    97.6 1949.33   143.2 1948.29   165.1 1944.16   184.3 1942.34   208.4 1944.08
     231 1948.17   293.8 1946.41   318.9 1947.51   335.6 1945.93   371.5 1947.15
   391.3 1945.53   397.8  1944.7   402.7 1945.67   412.4 1952.95   419.6 1963.96
     424 1967.66   427.8 1968.98   442.8 1969.34   448.5  1972.7   501.3 1989.12
   515.2 1995.52     549 2014.69   558.6 2018.67   599.7 2041.56643.5116  2063.9
#Mann= 3 ,-1 , 0
       0      .1       0   391.3    .045       0   402.7      .1       0
#XS Ineff= 2 , 0
             250    1950
Permanent Ineff=
       F       F
Bank Sta=391.3,402.7
XS Rating Curve= 0 ,0
Exp/Cntr(USF)=0,0
Exp/Cntr=0.3,0.1

Type RM Length L Ch R = 1 ,11004   ,145.5,121.6,98.8
XS GIS Cut Line= 4
2038505.05737828257568.0560796232038257.44354252257377.659783598
2038157.80610263257283.9413995442037985.16697411257181.344431737
#Sta/Elev= 30
       0  1983.9    42.6 1961.51    51.8  1960.9    63.3 1957.62      69 1956.84
   155.2 1945.99   170.9 1945.23   187.4  1940.1   195.8 1939.26   203.6 1940.09
   208.5 1942.54   212.3 1943.44   225.1 1942.54   237.2 1943.85   330.5 1943.43
   341.6 1942.88   347.6 1941.35   357.9  1940.4   369.5 1941.46   379.1 1943.88
   392.7 1945.16   401.7 1947.66   426.3 1959.73   442.2 1960.33   450.9 1967.46
     470 1977.27     531 2018.12   553.9 2032.64   584.8  2048.5 649.963 2078.43
#Mann= 3 ,-1 , 0
       0      .1       0   347.6    .045       0   369.5      .1       0
#XS Ineff= 2 , 0
             250 1948.57
Permanent Ineff=
       F       F
Bank Sta=347.6,369.5
XS Rating Curve= 0 ,0
Exp/Cntr(USF)=0,0
Exp/Cntr=0.5,0.3

Type RM Length L Ch R = 1 ,10882   ,76.3,98.6,116.4
XS GIS Cut Line= 4
2038602.72179956257446.715435006  2038371.878622257317.482715942
2038274.21420072257267.1707413452038026.60036496257163.587264232
#Sta/Elev= 30
       0 1986.73    14.3 1980.42    64.9 1963.13    79.2 1960.79    86.7 1955.72
     101 1950.45   120.6 1945.93   128.1 1942.94     140 1943.49   149.2 1941.59
   160.1 1941.89     192 1936.59   209.5 1935.54   222.1 1939.28   229.6 1939.71
   285.6  1937.2     293 1936.26   332.3  1937.2   348.4 1939.04   366.8 1947.72
   413.3 1953.94   439.8 1954.42   444.8  1955.7   449.8 1958.17   498.7 1990.55
     520 2005.61   530.7  2010.8   565.1 2033.77   604.9 2053.41642.8242 2068.23
#Mann= 3 ,-1 , 0
       0      .1       0   285.6    .045       0   332.3      .1       0
#XS Ineff= 2 , 0
             250 1943.84
Permanent Ineff=
       F       F
Bank Sta=285.6,332.3
XS Rating Curve= 0 ,0
Exp/Cntr(USF)=0,0
Exp/Cntr=0.5,0.3

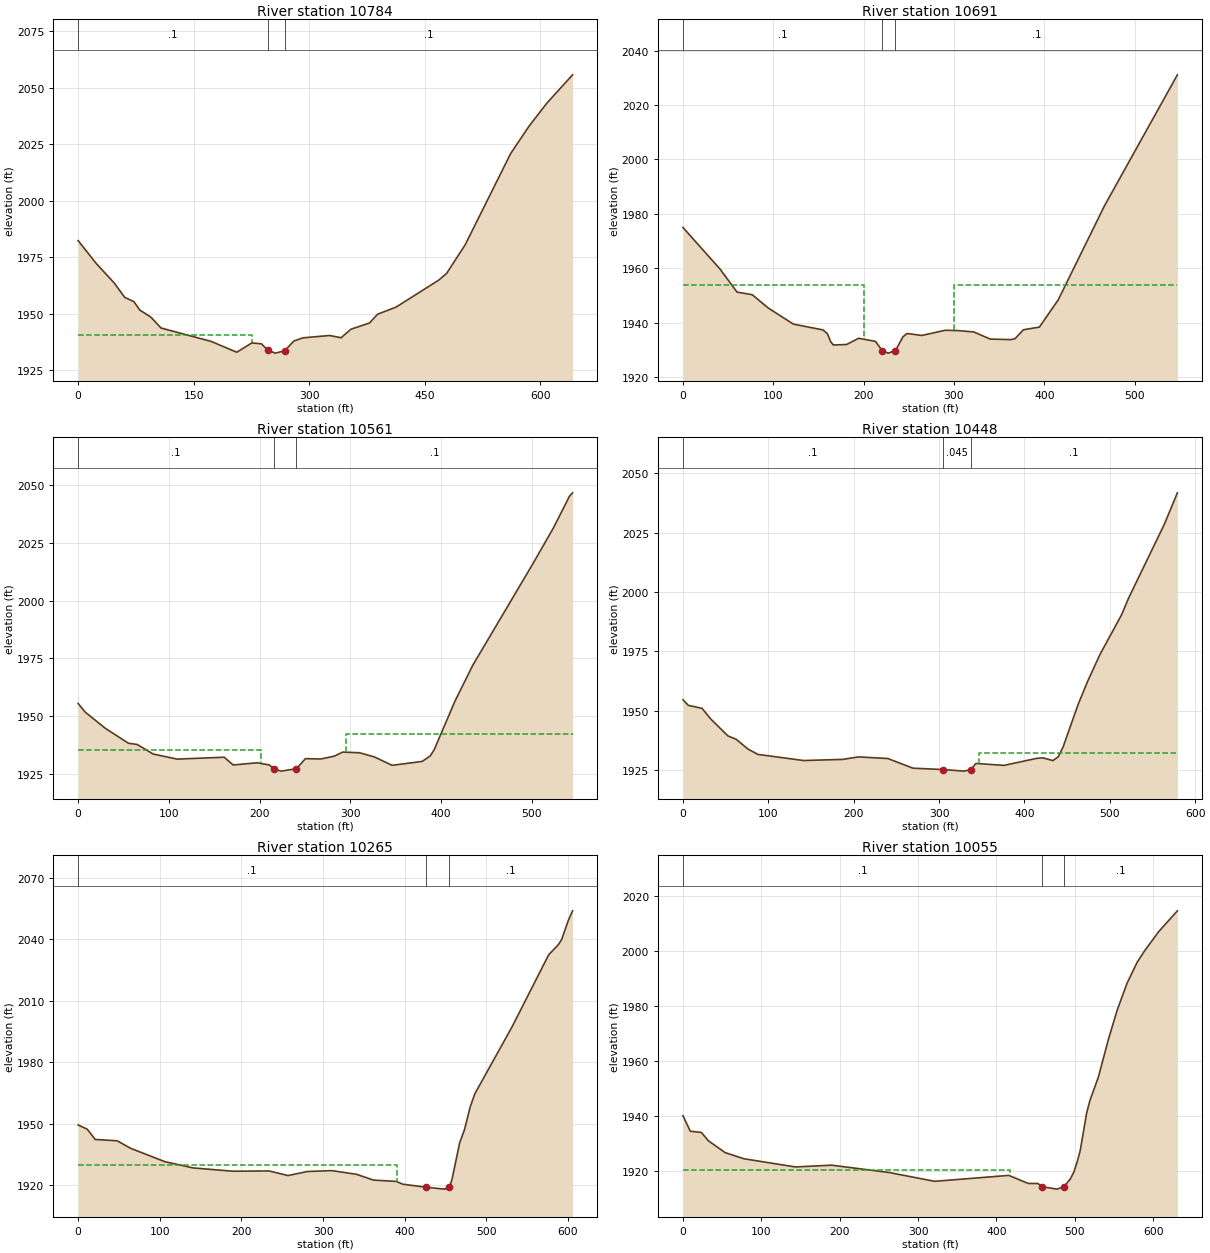
Type RM Length L Ch R = 1 ,10784   ,88.6,93.3,96.4
XS GIS Cut Line= 4
2038647.11471832257402.3225162442038452.77238508257299.725548437
2038364.97305686257242.5080086992038063.10120927257143.857078116
#Sta/Elev= 30
       0 1982.41    23.3 1972.37    46.8 1963.68    60.5 1957.31    72.5 1955.42
    80.1 1951.68    94.5 1948.56   107.6 1943.76   172.9 1937.82     206 1933.04
   225.5 1937.15     238 1936.78   246.8 1933.85   256.1 1932.65   268.2 1933.67
   280.1 1937.98   291.8  1939.4   326.6 1940.45   341.5 1939.46   354.3 1943.22
   378.4 1945.97   388.8 1949.84   412.9    1953   468.2  1964.9   478.6 1967.92
   502.7 1980.57   561.8 2020.94   585.5 2032.95   608.6 2043.12642.1416  2055.7
#Mann= 3 ,-1 , 0
       0      .1       0   246.8    .045       0   268.2      .1       0
#XS Ineff= 2 , 0
          225.64 1940.59
Permanent Ineff=
       F       F
Bank Sta=246.8,268.2
XS Rating Curve= 0 ,0
Exp/Cntr(USF)=0,0
Exp/Cntr=0.5,0.3

Type RM Length L Ch R = 1 ,10691   ,139,130,116.5
XS GIS Cut Line= 4
2038666.84490444257371.7407277632038528.73360162257251.386592451
2038438.96125479257179.3714131262038260.40307044257005.745775299
#Sta/Elev= 30
       0 1975.03    40.9 1959.82    59.9  1951.3    76.7 1950.34    94.4 1945.46
   122.3 1939.54     155 1937.42   159.8 1936.07   163.7 1932.99   166.5 1931.89
   181.1 1932.05   194.5 1934.35   213.1 1933.21   220.61929.796   227.1 1928.89
  235.251929.798   243.5 1934.88   248.1  1936.1   264.5 1935.38   290.5  1937.3
   304.7 1937.16   321.9 1936.67   340.2 1934.05   363.1 1933.85   367.6 1934.19
   376.8 1937.46   394.6 1938.46   415.5  1948.5   466.5 1982.92547.3375 2031.09
#Mann= 3 ,-1 , 0
       0      .1       0   220.6    .045       0  235.25      .1       0
#XS Ineff= 2 , 0
             200 1953.91     300         1953.91
Permanent Ineff=
       F       F
Bank Sta=220.6,235.25
XS Rating Curve= 0 ,0
Exp/Cntr(USF)=0,0
Exp/Cntr=0.3,0.1

Type RM Length L Ch R = 1 ,10561   ,114.2,112.4,109.9
XS GIS Cut Line= 4
2038737.17384031257240.0460835992038640.64606252257131.018305838
2038514.25717366 257111.573861392038311.24028477 256931.25505121
#Sta/Elev= 30
       0  1955.4     8.1 1951.58      30 1944.65    55.5 1938.17    65.1 1937.66
    82.6 1933.52   109.1  1931.3     161 1932.12   170.9 1928.76   197.5 1929.71
   210.8 1928.76   216.11926.963   223.7 1926.09   240.6 1927.12   250.6 1931.51
   267.2 1931.34   282.3 1932.57   291.7 1934.35   310.2 1934.05   326.5 1932.25
   346.1 1928.61   379.3 1930.31   388.1 1932.67   392.4 1935.33   415.2  1956.3
     435 1972.01   500.8 2015.72   524.1 2031.71   541.6 2045.33     545 2046.78
#Mann= 3 ,-1 , 0
       0      .1       0   216.1    .045       0   240.6      .1       0
#XS Ineff= 2 , 0
          201.77 1935.06  294.94         1941.98
Permanent Ineff=
       F       F
Bank Sta=216.1,240.6
XS Rating Curve= 0 ,0
Exp/Cntr(USF)=0,0
Exp/Cntr=0.3,0.1

Type RM Length L Ch R = 1 ,10448   ,164.7,182.8,198.7
XS GIS Cut Line= 4
 2038829.6189399257186.2769782662038618.50594846257010.678321828
2038515.90898065257003.7727566882038343.26985213256899.202770269
#Sta/Elev= 30
       0  1954.6     6.3 1952.24    22.3 1950.99    33.1  1946.3    52.9 1939.32
    62.2    1938    76.2 1933.83    87.8 1931.59   141.4    1929   187.1 1929.48
   205.8 1930.53     240 1929.86   269.5 1925.78  304.861925.203   329.5 1924.54
  337.131925.202   343.3 1927.77   376.1 1926.96   414.3 1929.91     422 1930.12
   433.5 1928.97   439.7 1930.62   445.4 1934.76   462.8 1952.46     474 1962.26
   488.4 1973.57     514 1990.47   521.8 1997.19   563.9 2028.47579.2656 2041.76
#Mann= 3 ,-1 , 0
       0      .1       0  304.86    .045       0  337.13      .1       0
#XS Ineff= 2 , 0
                          347.23          1932.1
Permanent Ineff=
       F       F
Bank Sta=304.86,337.13
XS Rating Curve= 0 ,0
Exp/Cntr(USF)=0,0
Exp/Cntr=0.3,0.1

Type RM Length L Ch R = 1 ,10265   ,207.5,210.3,213.3
XS GIS Cut Line= 4
2038905.58015645257123.1403826932038604.69481817256860.728907342
2038534.65265746256790.6867466282038450.79936646256723.604113831
#Sta/Elev= 30
       0 1949.42    11.1 1947.38      21 1942.34    47.9  1941.7    64.2 1938.04
   106.1 1931.54   140.8 1928.47   189.7 1926.85   233.9 1926.99   257.2 1924.74
   280.6 1926.71   310.7 1927.15   340.9 1925.37   361.8 1922.52   389.7 1921.89
   397.8 1920.51  426.531919.035   448.8 1918.12  454.841919.036     458 1922.89
   467.3  1940.6   473.3 1947.15   480.2 1958.14   485.9  1964.6   531.5 1997.26
   576.5  2032.5   587.9 2037.22   592.2 2039.82   600.5 2049.25605.6782 2053.89
#Mann= 3 ,-1 , 0
       0      .1       0  426.53    .045       0  454.84      .1       0
#XS Ineff= 2 , 0
          390.34    1930
Permanent Ineff=
       F       F
Bank Sta=426.53,454.84
XS Rating Curve= 0 ,0
Exp/Cntr(USF)=0,0
Exp/Cntr=0.3,0.1

Type RM Length L Ch R = 1 ,10055   ,176.8,188.6,200.4
XS GIS Cut Line= 4
2039013.10967079257062.9633150372038746.75215821256712.752511467
2038696.44018362256647.642897282 2038592.8567065 256615.08809019
#Sta/Elev= 30
       0 1940.04     9.4  1934.4    23.5 1933.96    32.5 1930.91    53.9 1926.62
    77.8 1924.39   143.7 1921.41   189.7 1922.06   263.3 1919.38     321 1916.19
   415.8 1918.34   440.5 1915.42     453 1915.38  458.281914.218   477.4 1913.35
  485.931914.217   494.4  1917.1   498.9 1919.64   503.4 1923.63   506.9  1927.4
   515.1 1941.06   519.3 1945.62   529.9 1953.96     543 1967.94   554.1 1978.46
   566.6 1988.18   579.6 1995.86   589.2 2000.05     607 2006.96630.8553 2014.52
#Mann= 3 ,-1 , 0
       0      .1       0  458.28    .045       0  485.93      .1       0
#XS Ineff= 2 , 0
          416.64 1920.14
Permanent Ineff=
       F       F
Bank Sta=458.28,485.93
XS Rating Curve= 0 ,0
Exp/Cntr(USF)=0,0
Exp/Cntr=0.3,0.1

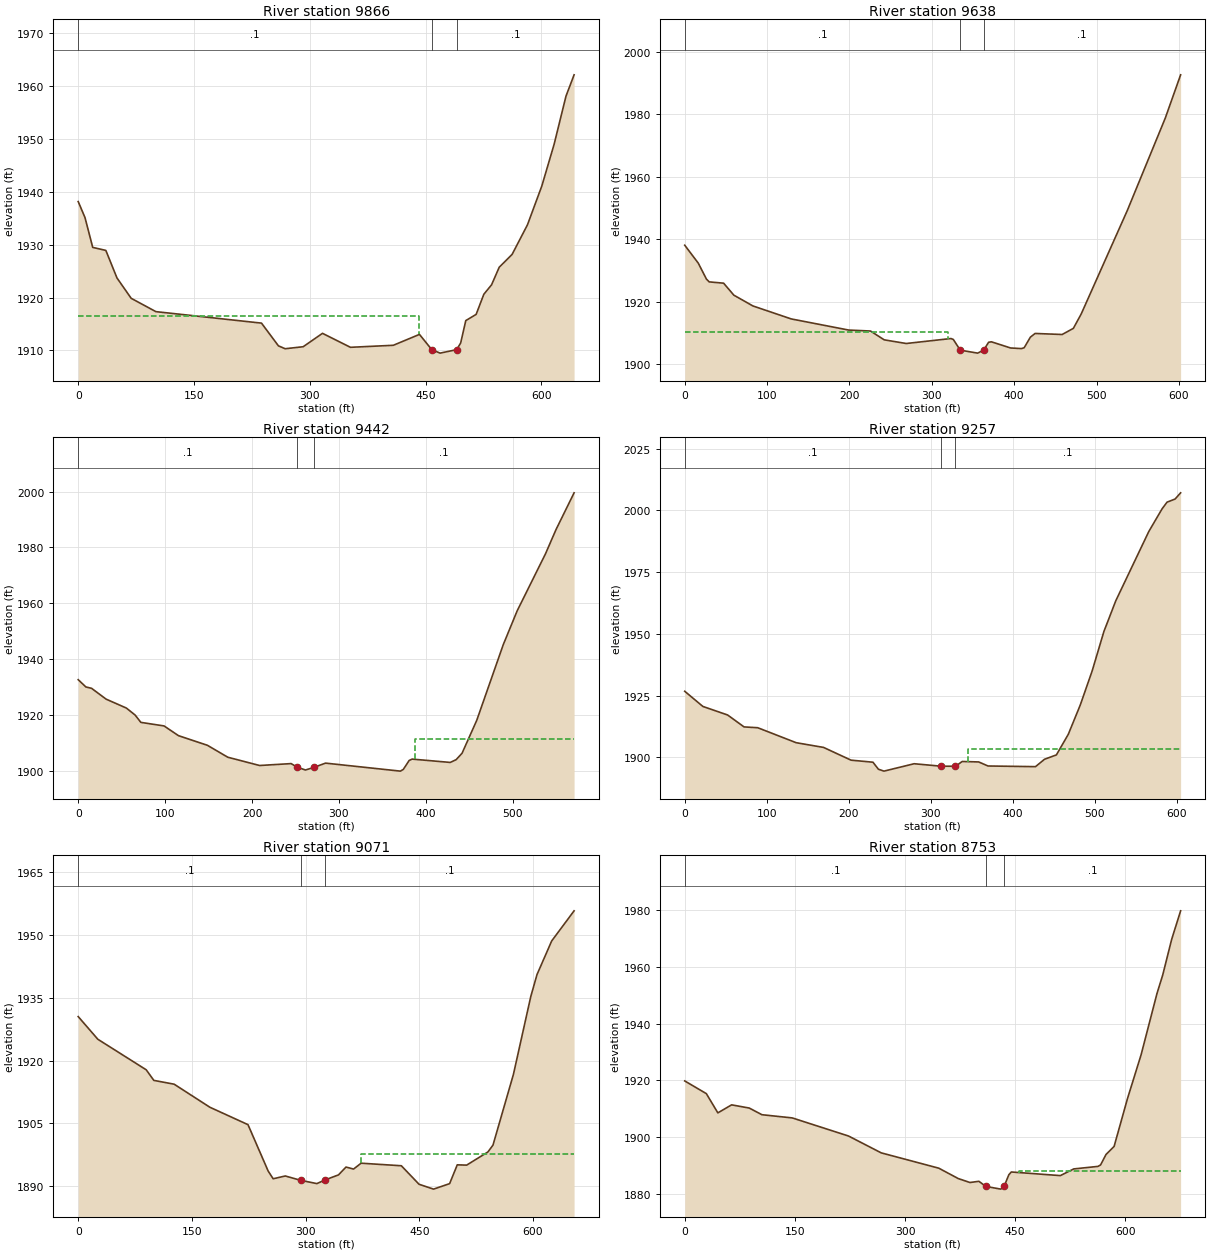
Type RM Length L Ch R = 1 ,9866    ,217.5,228.6,236.7
XS GIS Cut Line= 4
2039080.19230358257040.2736010032038901.63411923256644.683369365
2038885.84997034256559.8435690632038866.11978422256439.489433752
#Sta/Elev= 30
       0 1938.14     8.8 1935.11    18.8 1929.48    35.8 1928.91    50.2 1923.71
    68.6 1919.86   100.6 1917.34   237.4 1915.17   259.3 1910.88     268 1910.33
   291.4 1910.71   316.4 1913.24   352.6  1910.6   408.1 1910.98     442 1913.04
  457.961910.159   468.7  1909.5  490.291910.158   495.4 1911.43     502 1915.65
   515.4 1916.82   525.4 1920.63   535.4 1922.41   545.3 1925.73     562 1928.16
   581.9 1933.75   600.5 1941.09   616.4 1948.96   631.8 1958.07642.2777 1962.09
#Mann= 3 ,-1 , 0
       0      .1       0  457.96    .045       0  490.29      .1       0
#XS Ineff= 2 , 0
          441.83 1916.61
Permanent Ineff=
       F       F
Bank Sta=457.96,490.29
XS Rating Curve= 0 ,0
Exp/Cntr(USF)=0,0
Exp/Cntr=0.3,0.1

Type RM Length L Ch R = 1 ,9638    ,201.8,195.6,191.7
XS GIS Cut Line= 4
2039115.70663859257030.408507945 2039082.1653222256810.416932745
2039113.73361998256636.7912949182039095.97645248256434.556887223
#Sta/Elev= 30
       0 1938.14    16.4 1932.42    26.4 1927.28    29.7 1926.41    47.2    1926
    59.6 1922.17    82.8 1918.71   129.3 1914.56     199    1911   225.5 1910.69
   242.2 1907.87   268.9  1906.7   323.2 1908.29   326.1 1907.98  334.471904.571
   355.6 1903.62  362.88 1904.57   368.9 1907.09   372.3 1907.24   395.6 1905.27
   408.8 1905.07   412.1 1905.35   419.6 1908.72   425.3 1909.91   458.2 1909.58
   471.8 1911.54   481.3 1916.13   537.3 1949.25   583.4 1978.81602.0185 1992.65
#Mann= 3 ,-1 , 0
       0      .1       0  334.47    .045       0  362.88      .1       0
#XS Ineff= 2 , 0
          320.09 1910.51
Permanent Ineff=
       F       F
Bank Sta=334.47,362.88
XS Rating Curve= 0 ,0
Exp/Cntr(USF)=0,0
Exp/Cntr=0.3,0.1

Type RM Length L Ch R = 1 ,9442    ,191.1,185.1,182.8
XS GIS Cut Line= 4
2039332.73868588256999.8267194642039296.23784156256795.619293157
2039279.46718336256643.6968600592039229.15520877256439.489433752
#Sta/Elev= 30
       0 1932.75     8.8 1930.16    15.4 1929.66    32.1  1925.8    55.4 1922.61
    65.4 1920.14    72.1 1917.49    98.8 1916.22   115.4 1912.74   148.7  1909.3
   172.1 1905.04   208.7 1902.08     245 1902.76   251.7 1901.52   261.5 1900.47
   271.4 1901.43   284.6 1902.93   370.7 1900.07   374.1 1900.69   380.8 1903.87
   384.2 1904.37   428.1 1903.18   434.9 1904.17   441.7 1906.47   458.6 1918.23
   489.1 1945.27   505.1 1957.35   537.7 1977.74   549.8 1986.39570.6032 1999.53
#Mann= 3 ,-1 , 0
       0      .1       0   251.7    .045       0   271.4      .1       0
#XS Ineff= 2 , 0
                          387.72         1911.51
Permanent Ineff=
       F       F
Bank Sta=251.7,271.4
XS Rating Curve= 0 ,0
Exp/Cntr(USF)=0,0
Exp/Cntr=0.3,0.1

Type RM Length L Ch R = 1 ,9257    ,184,186.4,186.4
XS GIS Cut Line= 4
2039520.17545399256970.2314402892039467.89046078256704.860437021
2039441.25470952256619.0341274132039337.67123241256398.056042907
#Sta/Elev= 30
       0 1926.75    22.1 1920.61    52.2 1917.16    72.3 1912.32      89 1911.99
   135.8 1905.93   169.2 1904.02   202.7 1898.86   229.4 1898.03   236.1 1895.18
   242.8 1894.42   279.6 1897.41   312.3 1896.42     330 1896.39   338.2 1898.32
   358.3 1898.14   369.6  1896.5   427.5 1896.23   438.5 1899.22     453 1900.99
   467.5 1909.34     482 1921.12   496.6 1935.02   510.9 1950.97   525.4 1963.42
   565.6 1991.43   581.8 2000.62   587.8 2003.31   597.7  2004.6604.3881  2007.1
#Mann= 3 ,-1 , 0
       0      .1       0   312.3    .045       0     330      .1       0
#XS Ineff= 2 , 0
                          345.27         1903.33
Permanent Ineff=
       F       F
Bank Sta=312.3,330
XS Rating Curve= 0 ,0
Exp/Cntr(USF)=0,0
Exp/Cntr=0.3,0.1

Type RM Length L Ch R = 1 ,9071    ,311.6,317.4,294.8
XS GIS Cut Line= 4
2039693.80109181256957.4068193142039645.46213583256737.415244113
2039613.89383804256518.4101782182039566.54139136256316.175770523
#Sta/Elev= 30
       0 1930.49    25.9 1925.08    89.7 1917.79    99.8 1915.26   126.6 1914.35
   173.7 1908.85     224 1904.69   250.6 1893.62   257.2 1891.77   273.2 1892.44
   293.5  1891.4   314.9 1890.62   325.3 1891.47   343.4  1892.7   353.3 1894.57
   363.3 1894.09   373.2 1895.49   426.3 1894.88   449.7 1890.46   468.8  1889.3
     490 1890.61   500.1  1895.1   512.5 1895.03   540.5 1898.17   547.2  1899.8
   574.2 1916.71   597.1  1935.3   605.3 1940.53   624.7 1948.56654.2125 1955.74
#Mann= 3 ,-1 , 0
       0      .1       0   293.5    .045       0   325.3      .1       0
#XS Ineff= 2 , 0
                          372.94         1897.62
Permanent Ineff=
       F       F
Bank Sta=293.5,325.3
XS Rating Curve= 0 ,0
Exp/Cntr(USF)=0,0
Exp/Cntr=0.3,0.1

Type RM Length L Ch R = 1 ,8753    ,209.7,212.2,213.9
XS GIS Cut Line= 4
2039933.52285313256881.4456027642039825.99333879256540.113382947
 2039792.4520224256419.7592476352039707.61222209256247.120119115
#Sta/Elev= 30
       0 1919.82    29.4 1915.34    45.1 1908.55    63.8 1911.38    87.9 1910.25
   105.1  1907.9   146.4 1906.77     223 1900.38   267.5 1894.44   345.9 1889.03
   372.3 1885.38   388.3 1883.98   400.5  1884.4  409.961882.601   430.3 1881.64
  434.83  1882.6   441.3 1886.73   444.7 1887.69   511.4 1886.41   529.7 1888.77
   562.6 1889.66   566.2 1890.18   573.6 1893.87   584.6 1896.71   602.8 1913.57
   621.4 1929.09     643 1950.69   650.8 1957.21     663  1969.8675.1688 1979.85
#Mann= 3 ,-1 , 0
       0      .1       0  409.96    .045       0  434.83      .1       0
#XS Ineff= 2 , 0
                           454.7            1888
Permanent Ineff=
       F       F
Bank Sta=409.96,434.83
XS Rating Curve= 0 ,0
Exp/Cntr(USF)=0,0
Exp/Cntr=0.3,0.1