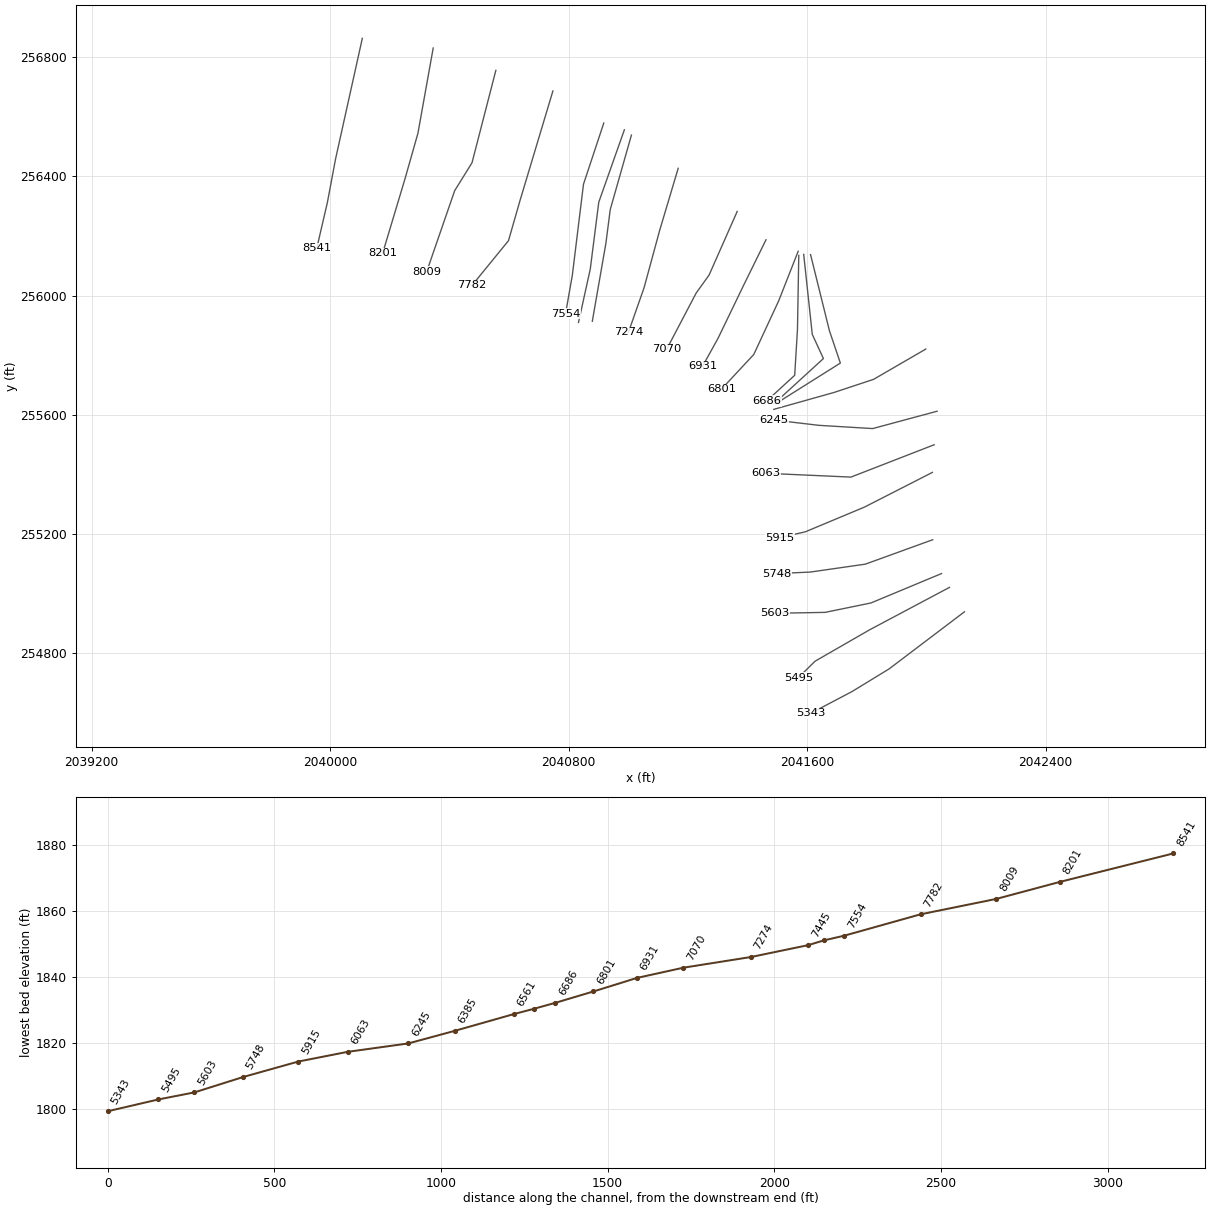
HEC-RAS study HNGRDCK_2.prj: HNGRDCK_2

--- HNGRDCK_2.g01 (geometry) --- (continued)

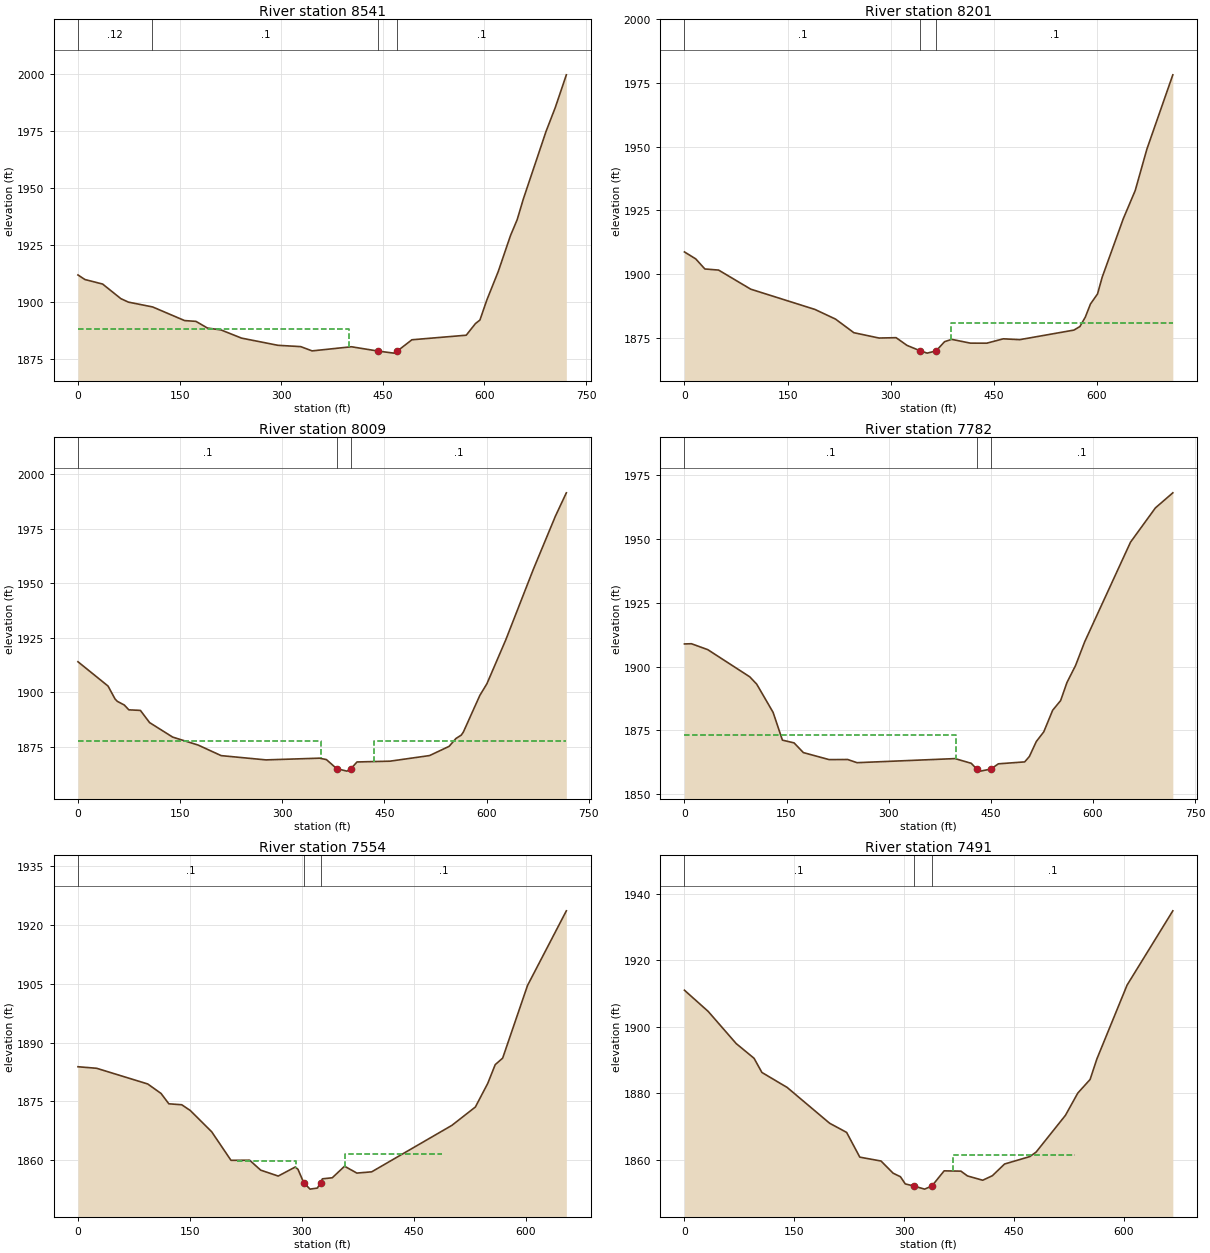
Type RM Length L Ch R = 1 ,8541    ,334.3,339.6,334.6
XS GIS Cut Line= 4
2040108.13500026256862.7019259542040018.36265343256458.233110563
2039990.74039287256311.2432239942039955.22605786 256158.33428159
#Sta/Elev= 30
       0 1911.78    10.3 1909.78    36.4  1907.8    63.3 1901.41    74.5 1899.88
   110.3 1897.76   157.4  1891.8   174.2 1891.45     191 1888.54   211.2 1887.69
   241.4 1884.12   295.2 1880.96   328.8 1880.39   345.6 1878.52   403.6 1880.33
  443.261878.423   466.2 1877.54  471.291878.423   492.9 1883.39   573.1 1885.39
   586.6 1890.46   593.3 1892.03   603.4 1900.73   620.3 1913.26   638.4 1929.03
   648.3 1936.02   657.3    1945     691 1974.76   704.5 1985.11720.8534 1999.45
#Mann= 4 ,-1 , 0
       0     .12       0     110      .1       0  443.26    .045       0
  471.29      .1       0
#XS Ineff= 2 , 0
           399.4 1888.24
Permanent Ineff=
       F       F
Bank Sta=443.26,471.29
XS Rating Curve= 0 ,0
Exp/Cntr(USF)=0,0
Exp/Cntr=0.3,0.1

Type RM Length L Ch R = 1 ,8201    ,197.1,191.9,185.4
XS GIS Cut Line= 4
2040345.88374297256830.1471188612040294.58525906 256544.05942017
2040251.17884961256391.1504777662040176.20414236256141.563623391
#Sta/Elev= 30
       0 1908.66    16.4 1905.94    29.7 1901.97    49.7 1901.53    96.4 1894.03
   189.7 1886.08   219.7 1882.28   246.4 1876.93     283 1874.84   307.8 1874.98
   323.8 1871.93   343.21869.783     353 1868.91  365.961869.783   378.3 1873.41
   388.6 1874.32   415.9 1872.83   439.7 1872.82   463.7 1874.53   487.6  1874.2
   566.4 1877.96   575.1 1879.36     583 1883.09   590.4 1888.19   600.7 1892.17
   607.5 1898.75   638.3  1921.8   655.5 1932.77   672.5 1949.06710.2057 1978.23
#Mann= 3 ,-1 , 0
       0      .1       0   343.2    .045       0  365.96      .1       0
#XS Ineff= 2 , 0
                          387.93         1880.71
Permanent Ineff=
       F       F
Bank Sta=343.2,365.96
XS Rating Curve= 0 ,0
Exp/Cntr(USF)=0,0
Exp/Cntr=0.3,0.1

Type RM Length L Ch R = 1 ,8009    ,219.6,227.1,230.8
XS GIS Cut Line= 4
2040556.01022511256755.1724116182040476.10297134256445.408489587
2040417.89892229256351.6901055332040324.18053824256080.400046429
#Sta/Elev= 30
       0 1913.95    44.2 1902.78    54.4 1896.89    57.8 1895.76      68 1894.09
    74.7 1891.86    91.7  1891.6   105.2    1886   139.1 1879.34   176.5 1875.68
   210.3 1870.83   276.1 1868.87     355 1869.66   364.9    1869     3801864.844
     395 1863.71     4011864.846   409.8 1867.92   458.3 1868.28   516.4 1870.86
     545 1875.07   555.1 1878.69   562.9 1880.26   565.9 1881.59   590.2 1898.49
   600.6 1903.86   628.3 1924.01   668.6 1956.27   701.2 1980.82717.2477 1991.53
#Mann= 3 ,-1 , 0
       0      .1       0     380    .045       0     401      .1       0
#XS Ineff= 2 , 0
          357.13  1877.5     435          1877.5
Permanent Ineff=
       F       F
Bank Sta=380,401
XS Rating Curve= 0 ,0
Exp/Cntr(USF)=0,0
Exp/Cntr=0.3,0.1

Type RM Length L Ch R = 1 ,7782    ,222.5,228.5,229.4
XS GIS Cut Line= 4
2040747.39303044 256686.116760212040636.90398819256318.148789134
2040598.43012526256183.9835235412040476.10297134256034.034109055
#Sta/Elev= 30
       0 1908.88    10.3 1908.96    34.3 1906.64      96 1895.98   106.2  1893.1
   130.2 1882.07   143.9 1871.18     161  1870.1   174.7 1866.29   212.4 1863.55
   239.8 1863.58   253.5 1862.34   397.4 1863.94   421.2  1862.1  429.271859.858
   434.9 1859.03  450.191859.859     461 1861.89   499.7 1862.65   506.6 1864.77
   516.8 1870.64   527.8 1874.45   540.8 1882.89   552.5 1886.68   561.8 1893.77
   574.4 1900.41   587.9 1909.75   655.1 1948.75   691.7  1962.2717.2878 1968.11
#Mann= 3 ,-1 , 0
       0      .1       0  429.27    .045       0  450.19      .1       0
#XS Ineff= 2 , 0
           399.4 1873.22
Permanent Ineff=
       F       F
Bank Sta=429.27,450.19
XS Rating Curve= 0 ,0
Exp/Cntr(USF)=0,0
Exp/Cntr=0.3,0.1

Type RM Length L Ch R = 1 ,7554    ,63.7,62.8,65.2
XS GIS Cut Line= 4
2040918.05914035256578.5872458742040849.98999825256373.393310261
2040812.50264463256067.5754254532040789.81293059255939.329215695
#Sta/Elev= 30
       0 1883.82      25 1883.43    93.5 1879.42   111.4 1876.99   121.8 1874.35
   139.1 1874.11   150.6 1872.63   179.2 1867.21   205.1 1859.91   230.1 1859.94
   244.9  1857.4   268.4 1855.89   291.2  1858.2   294.9  1857.6  302.49 1854.24
     311 1852.55   320.9 1852.82   325.1 1854.21   327.6 1855.18   340.8 1855.45
   357.3  1858.4   373.8 1856.65   393.7 1856.97   501.2 1868.85   532.6 1873.53
   549.2 1879.57   559.2 1884.36   569.2 1886.03   602.5 1904.59654.5345 1923.66
#Mann= 3 ,-1 , 0
       0      .1       0  302.49    .045       0   325.1      .1       0
#XS Ineff= 2 ,-1
  213.42  292.09 1859.68  358.26  487.321861.508
Permanent Ineff=
       F       T
Bank Sta=302.49,325.1
XS Rating Curve= 0 ,0
Exp/Cntr(USF)=0,0
Exp/Cntr=0.3,0.1

Type RM Length L Ch R = 1 ,7491    ,45.7,45.6,43.6
XS GIS Cut Line= 4
2040987.11479176 256555.897531842040901.28848215256313.216242605
2040872.67971228256088.2921208762040833.21934005 255909.73393652
#Sta/Elev= 30
       0 1911.04    32.4 1904.66    70.7 1894.95    95.1 1890.52   105.8 1886.25
   140.3 1881.73   198.3 1870.94   221.5 1868.18   239.5 1860.72   268.5 1859.55
     285 1855.88     295 1854.82   301.6 1852.65  313.291852.016     328 1851.08
  337.941852.016   354.7 1856.59   377.6  1856.5   386.6 1855.05   407.4 1853.76
   420.6 1855.13   437.2 1858.65   471.7 1860.89   480.2 1862.22   520.4 1873.34
   537.2 1880.03     554 1884.13   563.3 1890.33   604.5 1912.57667.0136 1934.97
#Mann= 3 ,-1 , 0
       0      .1       0  313.29    .045       0  337.94      .1       0
#XS Ineff= 1 ,-1
  367.29  533.431861.468
Permanent Ineff=
       T
Bank Sta=313.29,337.94
XS Rating Curve= 0 ,0
Exp/Cntr(USF)=0,0
Exp/Cntr=0.3,0.1

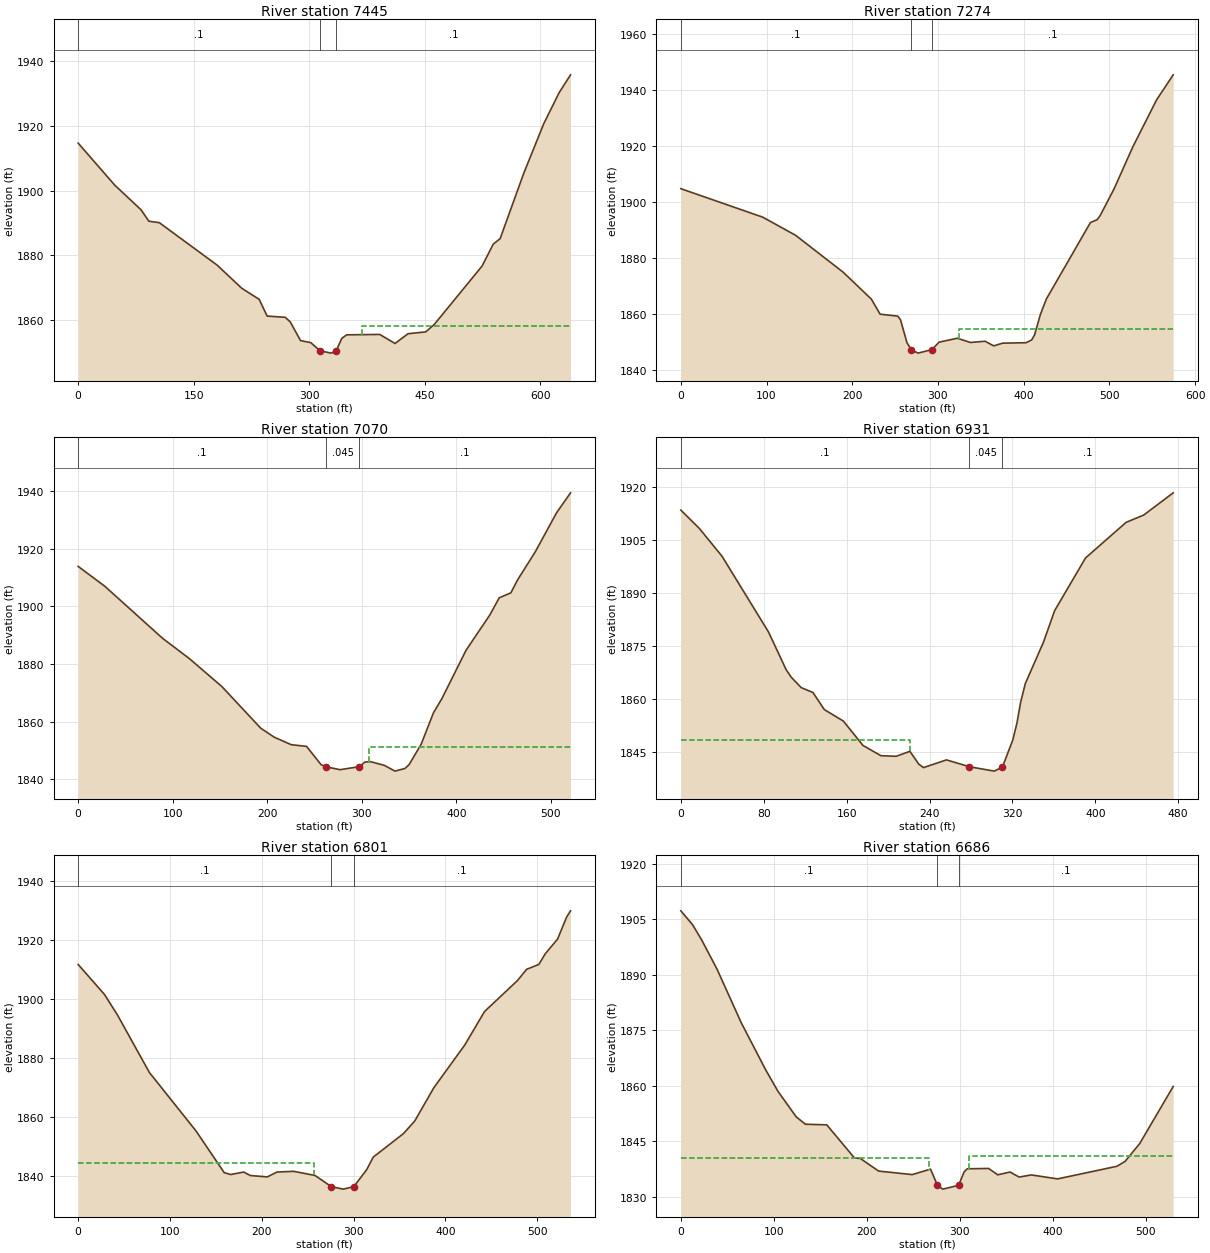
Type RM Length L Ch R = 1 ,7445    ,174.1,171.6,168.5
XS GIS Cut Line= 4
 2041010.7910151256538.1403643352040939.76234508 256288.55350996
2040924.96470549256174.1184304832040879.58527742255913.679973743
#Sta/Elev= 30
       0  1914.7    47.4 1901.71    81.6 1894.06    91.8 1890.52   105.4 1890.06
   180.5 1876.91   212.3 1869.77   235.1 1866.31   245.3 1861.15   268.9 1860.76
   275.5  1859.3   288.7 1853.55     302 1852.92  313.871850.418   328.4 1849.67
  335.141850.418   342.2 1854.22   348.5 1855.33   391.5 1855.46   411.4 1852.66
   428.3 1855.68   451.3 1856.25   462.4 1858.57   524.4 1876.63   538.9 1883.41
   547.9 1885.14   578.6 1905.42   604.5 1920.72   624.5 1930.34639.2472 1935.84
#Mann= 3 ,-1 , 0
       0      .1       0  313.87    .045       0  335.14      .1       0
#XS Ineff= 2 , 0
                          368.37         1857.97
Permanent Ineff=
       F       F
Bank Sta=313.87,335.14
XS Rating Curve= 0 ,0
Exp/Cntr(USF)=0,0
Exp/Cntr=0.3,0.1

Type RM Length L Ch R = 1 ,7274    ,210.7,203.4,196.2
XS GIS Cut Line= 4
2041167.64599473256426.6648127762041105.49590846256218.511349245
2041053.21091525256026.1420346082041000.92592204255877.179129428
#Sta/Elev= 30
       0 1904.84    95.6 1894.65   133.9 1888.18   189.3 1875.01   222.3 1865.36
   232.5 1859.98   253.1 1859.28   256.3 1857.98   263.8 1849.82  268.731847.319
   276.7 1846.06  293.021847.319   301.2 1849.97   322.6 1851.38   337.9 1849.86
   354.9 1850.31   365.1 1848.65   375.3 1849.62   402.8 1849.78   409.3 1850.76
   412.7 1852.57   419.5 1859.87   426.4 1865.36   477.9 1892.73   485.6 1893.73
   489.1 1895.15   505.6 1904.86   527.3 1919.76   555.1  1936.6574.4542 1945.53
#Mann= 3 ,-1 , 0
       0      .1       0  268.73    .045       0  293.02      .1       0
#XS Ineff= 2 , 0
                          324.74         1854.64
Permanent Ineff=
       F       F
Bank Sta=268.73,293.02
XS Rating Curve= 0 ,0
Exp/Cntr(USF)=0,0
Exp/Cntr=0.3,0.1

Type RM Length L Ch R = 1 ,7070    ,138.4,139,145.7
XS GIS Cut Line= 4
2041365.59540542256282.0462183032041271.25145822256068.612370539
2041227.94603984256008.2941092152041128.96222638255819.606214815
#Sta/Elev= 30
       0 1913.82    28.2 1906.92    89.1 1888.92   117.8 1881.78   151.9 1872.16
   193.2 1857.66   207.5 1854.55   225.4 1851.96   241.5 1851.39   256.8 1845.09
   261.91844.312     277  1843.3   297.4 1844.35   303.3 1845.95   309.2 1846.09
   323.9 1844.78   335.1  1842.8   345.6 1843.73   349.9 1845.01   362.7  1852.1
   375.8 1863.07   384.5 1867.86   410.2 1884.72   435.6 1897.09   445.3 1902.92
   457.6 1904.64   464.7 1909.14   483.3  1918.8     506 1932.45   520.7 1939.33
#Mann= 3 ,-1 , 0
       0      .1       0   261.9    .045       0   297.4      .1       0
#XS Ineff= 2 , 0
                          307.18         1851.11
Permanent Ineff=
       F       F
Bank Sta=261.9,297.4
XS Rating Curve= 0 ,0
Exp/Cntr(USF)=0,0
Exp/Cntr=0.3,0.1

Type RM Length L Ch R = 1 ,6931    ,131,130.8,132.7
XS GIS Cut Line= 4
2041462.16896302256186.9908249442041387.00312968 256034.15363048
2041301.81518522255857.5139221242041249.19910188255762.303866557
#Sta/Elev= 30
       0 1913.59    17.8 1908.43    39.8 1900.51    84.6  1879.1   101.7 1868.39
   106.6 1866.27   116.2 1863.34   127.5 1861.96   138.5 1857.12   156.8 1853.89
   175.8 1846.97   193.2 1844.06   207.8  1843.9   221.1  1845.3   229.7 1841.67
   234.2  1840.7   256.4 1842.88   278.5 1840.95   302.5  1839.7   310.4 1840.87
   320.3 1848.45   324.4  1853.3     328 1859.27   332.5 1864.51   349.9 1876.14
   360.8 1885.14   390.6 1900.05   429.7 1910.11   446.8  1912.2   475.2 1918.48
#Mann= 3 ,-1 , 0
       0      .1       0   278.5    .045       0   310.4      .1       0
#XS Ineff= 2 , 0
          221.12 1848.57
Permanent Ineff=
       F       F
Bank Sta=278.5,310.4
XS Rating Curve= 0 ,0
Exp/Cntr(USF)=0,0
Exp/Cntr=0.3,0.1

Type RM Length L Ch R = 1 ,6801    ,104.9,114.2,121.2
XS GIS Cut Line= 4
 2041570.1417915256148.4691885312041505.03217732255982.735625152
2041421.17888632255802.2044221842041312.66286268255685.796324096
#Sta/Elev= 30
       0 1911.76    28.7 1901.57    42.8 1894.64    77.6 1875.12   128.3 1855.33
   159.1 1841.16   166.2 1840.53   180.3 1841.37   187.5  1840.2     206 1839.72
   216.5 1841.37   234.6 1841.62   257.9 1840.22  275.821836.417   288.8 1835.58
  300.221836.418   314.2 1842.15   321.4 1846.44   354.2 1854.38   366.6 1858.68
   387.4 1869.97   421.1 1884.46   442.6  1895.8   478.5 1906.31   488.4  1910.1
   501.8 1911.78   508.8 1915.42   522.1 1920.33     532 1927.81536.2625 1929.94
#Mann= 3 ,-1 , 0
       0      .1       0  275.82    .045       0  300.22      .1       0
#XS Ineff= 2 , 0
          257.27 1844.41
Permanent Ineff=
       F       F
Bank Sta=275.82,300.22
XS Rating Curve= 0 ,0
Exp/Cntr(USF)=0,0
Exp/Cntr=0.3,0.1

Type RM Length L Ch R = 1 ,6686    ,56.7,64.5,77.2
XS GIS Cut Line= 4
2041572.08798028256134.4203175472041567.77298858255886.308294584
2041558.42383988255732.4069238182041464.61272396255646.346811505
#Sta/Elev= 30
       0 1907.24    12.6 1903.51    22.5 1899.35    38.9 1891.52    65.1 1876.98
    91.4 1864.27   104.5 1858.53   124.2 1851.61   134.1 1849.64     157 1849.48
   186.6 1840.59   193.1  1840.4   212.8    1837   248.9 1836.05   268.6 1837.53
  276.081833.144   281.8 1832.13  298.761833.145   304.8 1836.82   308.1 1837.62
   331.1 1837.71   340.9 1835.99   354.1 1836.75   363.9 1835.39   377.1 1835.96
   405.3 1834.89     469 1838.29   477.9 1839.62   493.6 1844.42529.6408 1859.83
#Mann= 3 ,-1 , 0
       0      .1       0  276.08    .045       0  298.76      .1       0
#XS Ineff= 2 , 0
          267.17 1840.51  309.45         1841.02
Permanent Ineff=
       F       F
Bank Sta=276.08,298.76
XS Rating Curve= 0 ,0
Exp/Cntr(USF)=0,0
Exp/Cntr=0.5,0.3

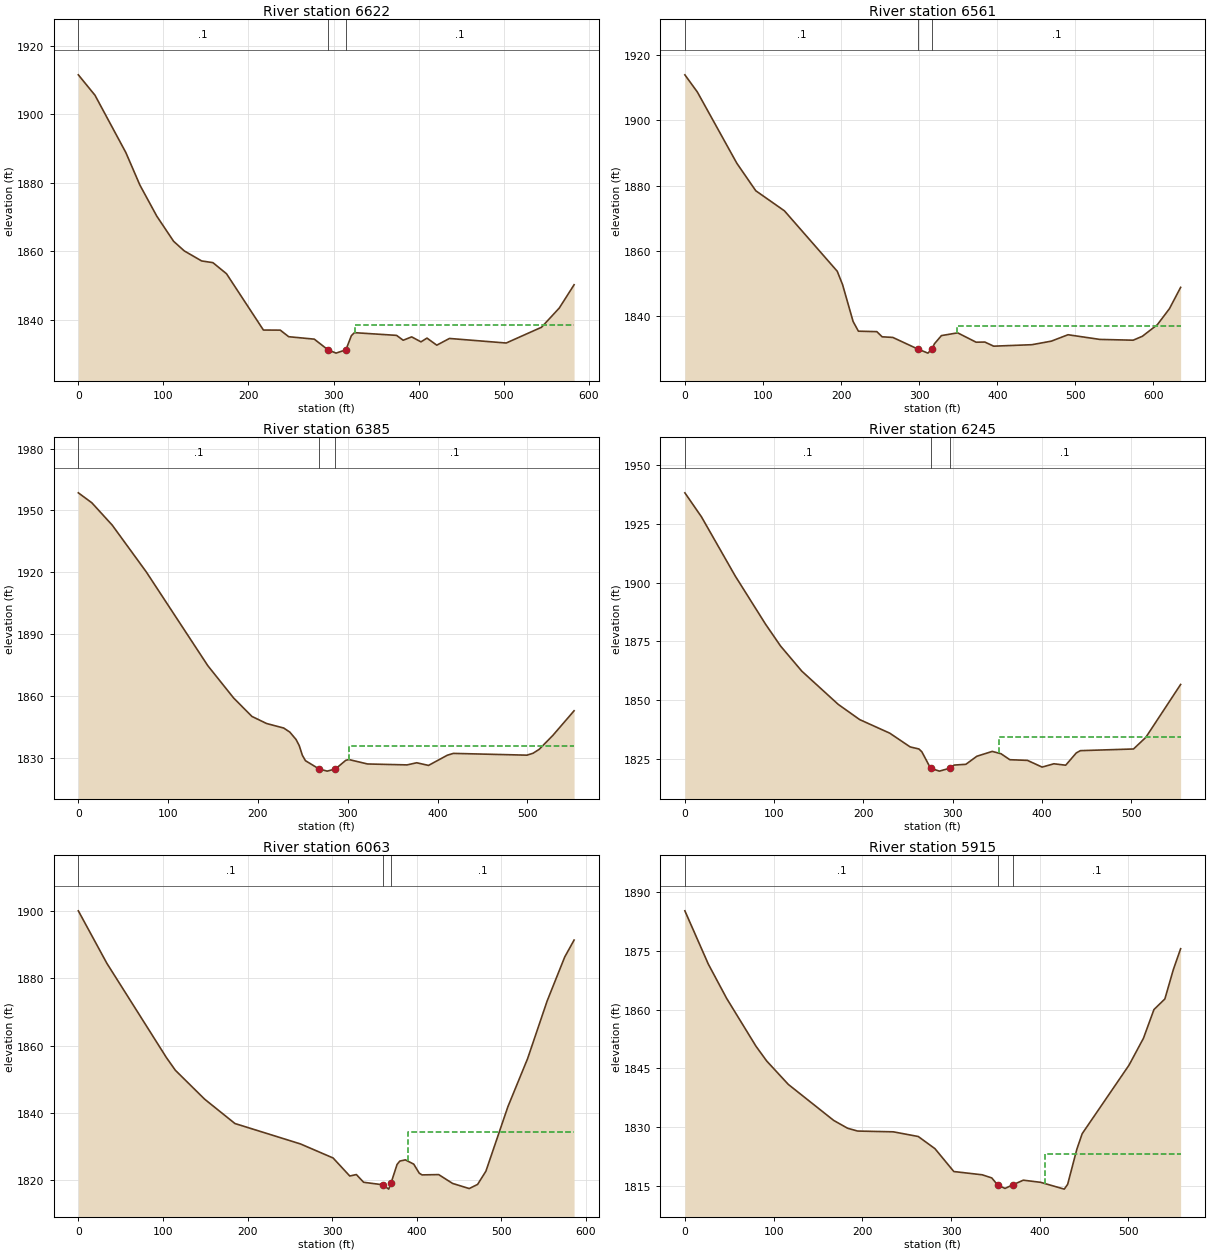
Type RM Length L Ch R = 1 ,6622    ,60.6,60.6,55
XS GIS Cut Line= 4
2041588.62878181256138.0161439672041617.39539317255869.767493053
2041654.79198793255788.5018159672041489.78350889255637.636920844
#Sta/Elev= 30
       0  1911.5    19.6 1905.54    55.9 1888.81    72.4 1879.33    92.2 1870.29
     112 1862.94   124.5 1860.14     145  1857.2   158.2 1856.71   174.2 1853.47
   217.6 1837.04   237.4 1837.02   247.3  1835.1   277.4 1834.39  293.381831.297
     303 1830.31  314.611831.294     321  1835.4   324.6 1836.28   374.1 1835.49
   381.9 1834.07   391.9 1835.05   402.8  1833.6   409.9 1834.69   421.4 1832.63
   436.3 1834.59     503 1833.26   544.5 1837.85   565.4 1843.46 582.824 1850.25
#Mann= 3 ,-1 , 0
       0      .1       0  293.38    .045       0  314.61      .1       0
#XS Ineff= 2 , 0
                          325.64         1838.64
Permanent Ineff=
       F       F
Bank Sta=293.38,314.61
XS Rating Curve= 0 ,0
Exp/Cntr(USF)=0,0
Exp/Cntr=0.5,0.3

Type RM Length L Ch R = 1 ,6561    ,207.3,176.1,148.4
XS GIS Cut Line= 4
 2041611.6420709256137.2969786832041674.92861588 255881.99330288
2041711.60604537255773.3993450042041493.93868609255636.518219291
#Sta/Elev= 30
       0 1913.93      16 1908.66    66.5 1886.86    90.8 1878.42   127.5 1872.27
   195.1 1853.77   201.9 1849.69   215.4 1838.39   222.2 1835.41   245.8 1835.27
   252.6 1833.69   266.2  1833.5  298.051829.971   311.2 1828.69  316.461829.969
   319.6 1831.56   328.5 1834.06   349.3  1834.9   372.9 1832.04   384.1 1832.08
   395.4 1830.82   444.3 1831.27   469.2 1832.36   490.6 1834.32   531.4 1832.89
     574 1832.65   585.8 1833.85     605  1837.4   620.5 1842.32634.7807 1848.83
#Mann= 3 ,-1 , 0
       0      .1       0  298.05    .045       0  316.46      .1       0
#XS Ineff= 2 , 0
                          348.43         1836.95
Permanent Ineff=
       F       F
Bank Sta=298.05,316.46
XS Rating Curve= 0 ,0
Exp/Cntr(USF)=0,0
Exp/Cntr=0.5,0.3

Type RM Length L Ch R = 1 ,6385    ,146.2,140.2,131.4
XS GIS Cut Line= 4
2041998.07355014255820.3049029682041823.07666438255718.822690677
2041690.43062312255674.8737011022041488.26527107255618.139550924
#Sta/Elev= 30
       0 1958.56    15.1 1953.71    37.8 1942.87    75.8 1920.13   144.2 1874.74
     173 1859.05   193.3 1850.15   209.6 1846.72   228.7 1844.52   235.5 1842.55
   242.5 1838.92     246 1835.97   249.4 1831.37   252.9 1828.69  268.06 1824.68
   277.1 1823.63  286.281824.682   297.8 1828.87   301.3 1829.24     322  1827.1
     366 1826.65   376.8 1827.68   389.9  1826.4   410.9 1831.35   417.7 1832.23
   499.5 1831.37   506.3 1832.29   513.1 1834.18   528.3 1840.92552.0057 1852.89
#Mann= 3 ,-1 , 0
       0      .1       0  268.06    .045       0  286.28      .1       0
#XS Ineff= 2 , 0
                          301.72         1835.92
Permanent Ineff=
       F       F
Bank Sta=268.06,286.28
XS Rating Curve= 0 ,0
Exp/Cntr(USF)=0,0
Exp/Cntr=0.3,0.1

Type RM Length L Ch R = 1 ,6245    ,186.8,181.7,182.1
XS GIS Cut Line= 4
2042036.16267444255611.9245422972041820.11713646255553.720493253
2041639.58593349255564.5720956172041489.63651901255582.329263122
#Sta/Elev= 30
       0  1938.3    18.6 1928.07    56.4 1902.91    90.3 1882.43   107.3 1873.03
   131.1 1862.34   171.8 1848.23   195.9 1841.73   229.6 1835.95   252.5 1830.09
   262.3 1829.21   265.6 1828.01  275.34 1821.02   285.3 1819.78  296.86 1821.02
   301.8 1822.36   314.9 1822.68   327.2 1826.11   344.5 1828.18   354.3 1827.19
   364.2 1824.64   383.9 1824.36   400.4  1821.5   413.6 1822.91   426.8  1822.3
   438.7 1827.55   443.3  1828.5   502.8 1829.21   516.6 1834.16555.6027 1856.69
#Mann= 3 ,-1 , 0
       0      .1       0  275.34    .045       0  296.86      .1       0
#XS Ineff= 2 , 0
                          352.44         1834.31
Permanent Ineff=
       F       F
Bank Sta=275.34,296.86
XS Rating Curve= 0 ,0
Exp/Cntr(USF)=0,0
Exp/Cntr=0.3,0.1

Type RM Length L Ch R = 1 ,6063    ,138.6,148.6,154.1
XS GIS Cut Line= 4
2042026.29758138255499.4624814322041747.11544783255390.946457791
2041614.92320085255396.8655136262041461.02774914255403.771078766
#Sta/Elev= 30
       0 1900.16    33.7 1884.53   104.1 1856.43   114.7 1852.64   149.3 1844.03
   185.1 1836.78   262.5  1830.7   301.1 1826.51   320.8 1821.14   328.6 1821.57
   337.2 1819.27     360 1818.52   366.8 1817.23   369.4 1818.91   376.7 1824.59
   379.9 1825.58   386.5 1825.95   396.4 1824.68   402.9 1821.99   406.2 1821.47
   425.9 1821.56   442.3 1818.93     462  1817.4   471.9 1818.64   481.7 1822.58
   507.7  1841.8     531 1856.14     554 1873.25   574.8 1886.38585.9053 1891.45
#Mann= 3 ,-1 , 0
       0      .1       0     360    .045       0   369.4      .1       0
#XS Ineff= 2 , 0
                           389.4         1834.12
Permanent Ineff=
       F       F
Bank Sta=360,369.4
XS Rating Curve= 0 ,0
Exp/Cntr(USF)=0,0
Exp/Cntr=0.3,0.1

Type RM Length L Ch R = 1 ,5915    ,172.3,166.4,160.2
XS GIS Cut Line= 4
2042020.37852555255406.730606684 2041792.4948759255290.322508596
2041594.20650543255207.4557269062041508.38019582255187.725540789
#Sta/Elev= 30
       0 1885.14    26.4 1871.59    47.1 1862.84    80.2 1850.65    92.2 1846.91
   116.6 1840.94   167.8 1831.76   183.4 1829.78   194.7 1829.06     235 1828.86
   263.1 1827.67   281.9 1824.58   303.2 1818.75   335.2 1817.92     346 1817.12
  352.661815.311   360.9 1814.45   370.4 1815.43   381.5 1816.55   401.1    1816
   427.7 1814.27   431.5 1815.49   441.9 1824.45   447.9 1828.39   500.7 1845.85
     517 1852.71   528.8    1860   541.1  1862.7   550.7 1870.21558.8665 1875.49
#Mann= 3 ,-1 , 0
       0      .1       0  352.66    .045       0   370.4      .1       0
#XS Ineff= 2 , 0
                          405.73         1823.18
Permanent Ineff=
       F       F
Bank Sta=352.66,370.4
XS Rating Curve= 0 ,0
Exp/Cntr(USF)=0,0
Exp/Cntr=0.3,0.1

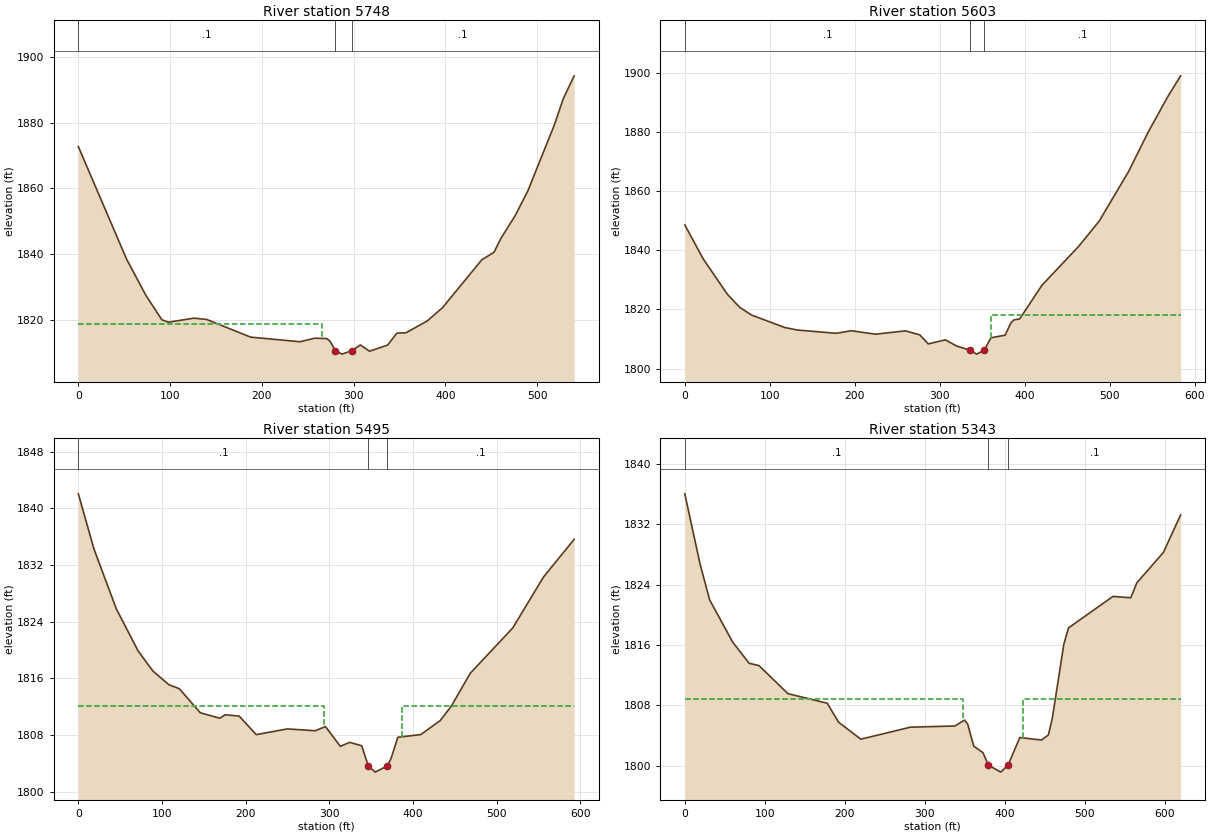
Type RM Length L Ch R = 1 ,5748    ,143.6,145.1,140.9
XS GIS Cut Line= 4
2042021.36503485255180.8199756482041795.45440382255098.939703264
2041609.99065432255072.3039520072041497.52859345255067.371405478
#Sta/Elev= 30
       0 1872.74    52.6 1838.45    73.5 1827.48      91    1820    98.2 1819.26
   125.9 1820.49   139.8  1820.1   187.7 1814.72   241.6 1813.31   257.6 1814.39
   270.8 1814.27   274.2 1813.48     2801810.636   287.4 1809.54   298.3 1810.64
   307.3 1812.34   317.2 1810.44     337 1812.29   347.1 1815.94     357 1816.04
   380.2 1819.65   396.8 1823.69   439.6 1838.26   452.9 1840.56   460.5 1844.83
   475.9 1851.67     490 1859.39   518.6 1879.29   528.4 1887.33540.2283 1894.28
#Mann= 3 ,-1 , 0
       0      .1       0     280    .045       0   298.3      .1       0
#XS Ineff= 2 , 0
          265.97 1818.65
Permanent Ineff=
       F       F
Bank Sta=280,298.3
XS Rating Curve= 0 ,0
Exp/Cntr(USF)=0,0
Exp/Cntr=0.3,0.1

Type RM Length L Ch R = 1 ,5603    ,99.9,108.3,112.6
XS GIS Cut Line= 4
2042050.96031403255067.3714054782041814.19808063254968.720474894
2041660.30262892254937.1521771082041490.62302831 254934.19264919
#Sta/Elev= 30
       0 1848.55    21.7 1837.06    50.1 1825.13    64.5 1820.73    78.5 1818.11
   117.6 1813.89   132.2 1813.05   178.1 1811.94   195.8  1812.8   224.3 1811.63
   259.6 1812.76   276.4 1811.42   286.4 1808.35   306.5 1809.73   319.9 1807.62
   335.71806.206   343.3  1804.9  352.321806.207   360.1 1810.42   376.8  1811.3
   383.5 1815.37   386.9 1816.43     394 1816.81   420.2 1828.18   462.9 1841.17
   487.4  1849.8     522 1866.55   544.9 1879.79   568.2  1891.9583.2977 1898.93
#Mann= 3 ,-1 , 0
       0      .1       0   335.7    .045       0  352.32      .1       0
#XS Ineff= 2 , 0
                          360.25         1818.06
Permanent Ineff=
       F       F
Bank Sta=335.7,352.32
XS Rating Curve= 0 ,0
Exp/Cntr(USF)=0,0
Exp/Cntr=0.3,0.1

Type RM Length L Ch R = 1 ,5495    ,152,151.8,153.5
XS GIS Cut Line= 4
2042077.59606528255021.005468104 2041810.2520434254878.948128064
2041626.76131252 254773.391632342041571.18944298254718.591594322
#Sta/Elev= 30
       0 1842.03    18.7 1834.24    45.3 1825.82    71.4 1819.86      89 1817.03
   108.3 1815.08   120.6 1814.53   145.7 1811.13   169.1 1810.36   175.4 1810.84
   192.2 1810.66   212.6 1808.04   249.7 1808.85   283.2 1808.59   295.3 1809.18
   313.1 1806.39   324.2 1806.95   338.6 1806.48   346.51803.627   354.7 1802.75
   369.21803.628   373.6 1804.64   381.8 1807.67   409.2 1808.05   432.3 1810.01
   445.5 1812.02   468.4 1816.71   519.2 1823.11   555.7 1830.26   592.5 1835.61
#Mann= 3 ,-1 , 0
       0      .1       0   346.5    .045       0   369.2      .1       0
#XS Ineff= 2 , 0
          293.86 1812.14   386.6         1812.14
Permanent Ineff=
       T       F
Bank Sta=346.5,369.2
XS Rating Curve= 0 ,0
Exp/Cntr(USF)=0,0
Exp/Cntr=0.3,0.1

Type RM Length L Ch R = 1 ,5343    ,161.5,167.9,175.3
XS GIS Cut Line= 4
2042127.90803988254939.1251957192041875.36165759254747.742390388
2041751.06148505254671.7811738392041611.68521579254598.389805001
#Sta/Elev= 30
       0 1836.01    19.2 1826.67    31.1 1821.97    59.9 1816.38    80.5 1813.58
    92.8 1813.27     129 1809.56   178.2 1808.29   192.2 1805.79   220.1 1803.53
   282.2 1805.12   337.8 1805.28   349.8 1806.06   353.7 1805.56   361.4 1802.61
   372.9 1801.75   379.71800.096   395.1 1799.17   404.31800.107     419 1803.75
     446 1803.42   454.7 1804.09   459.5 1806.21     474 1816.08   479.9 1818.26
   535.5 1822.43   557.8 1822.25   565.2 1824.21   598.6 1828.26   620.1 1833.22
#Mann= 3 ,-1 , 0
       0      .1       0   379.7    .045       0   404.3      .1       0
#XS Ineff= 2 , 0
          348.18 1808.89   422.9         1808.89
Permanent Ineff=
       F       F
Bank Sta=379.7,404.3
XS Rating Curve= 0 ,0
Exp/Cntr(USF)=0,0
Exp/Cntr=0.3,0.1