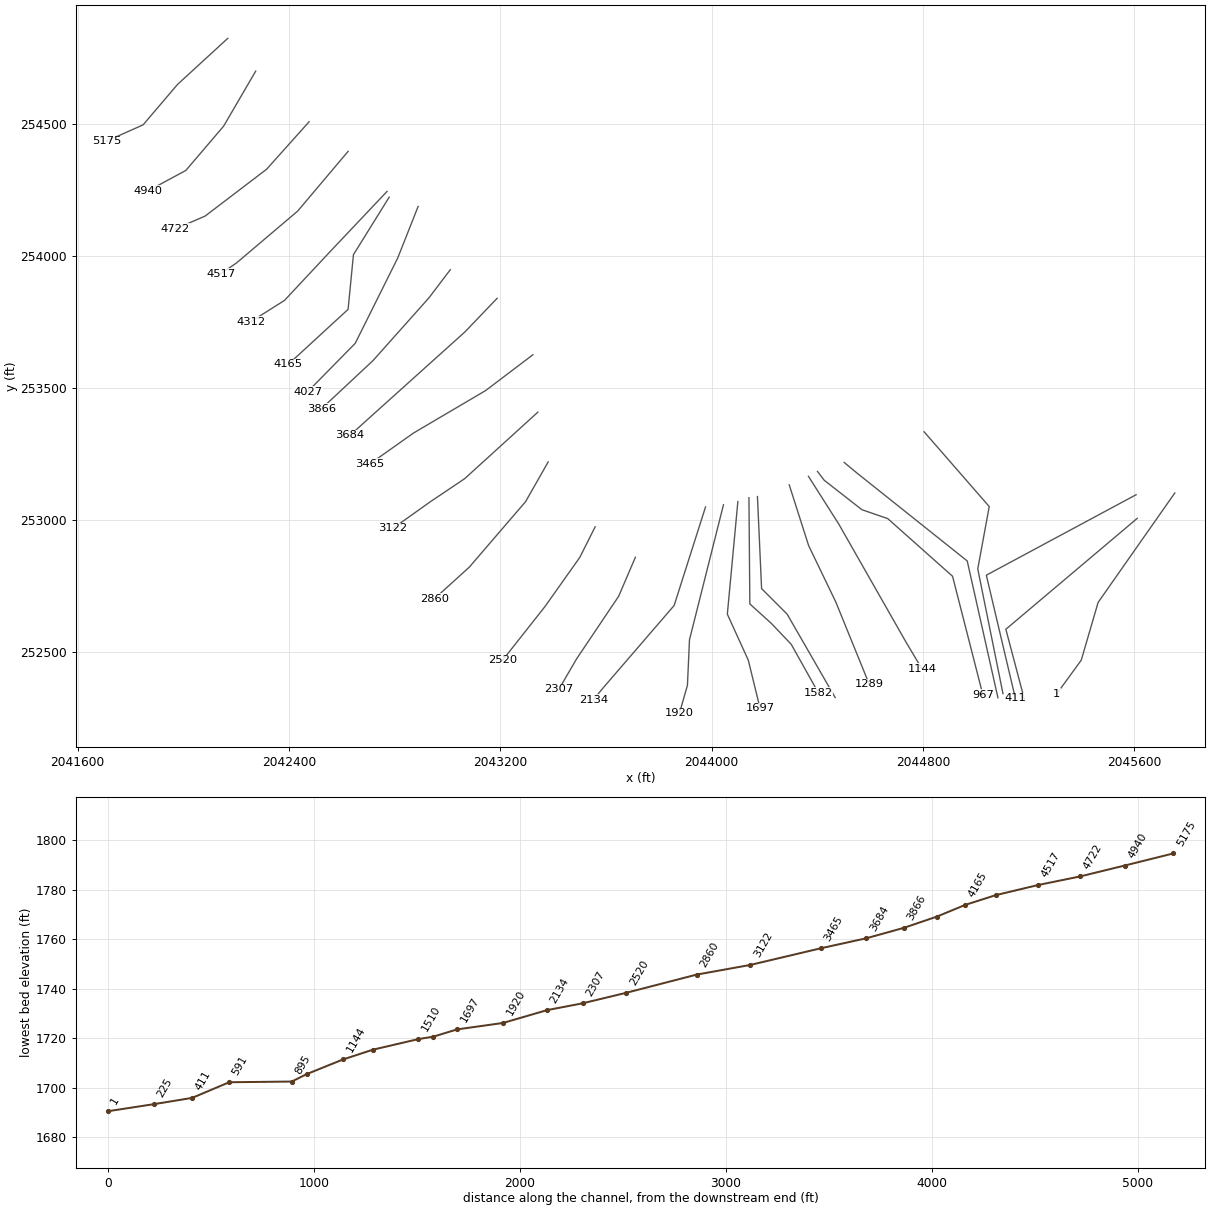
HEC-RAS study HNGRDCK_2.prj: HNGRDCK_2

--- HNGRDCK_2.g01 (geometry) --- (continued)

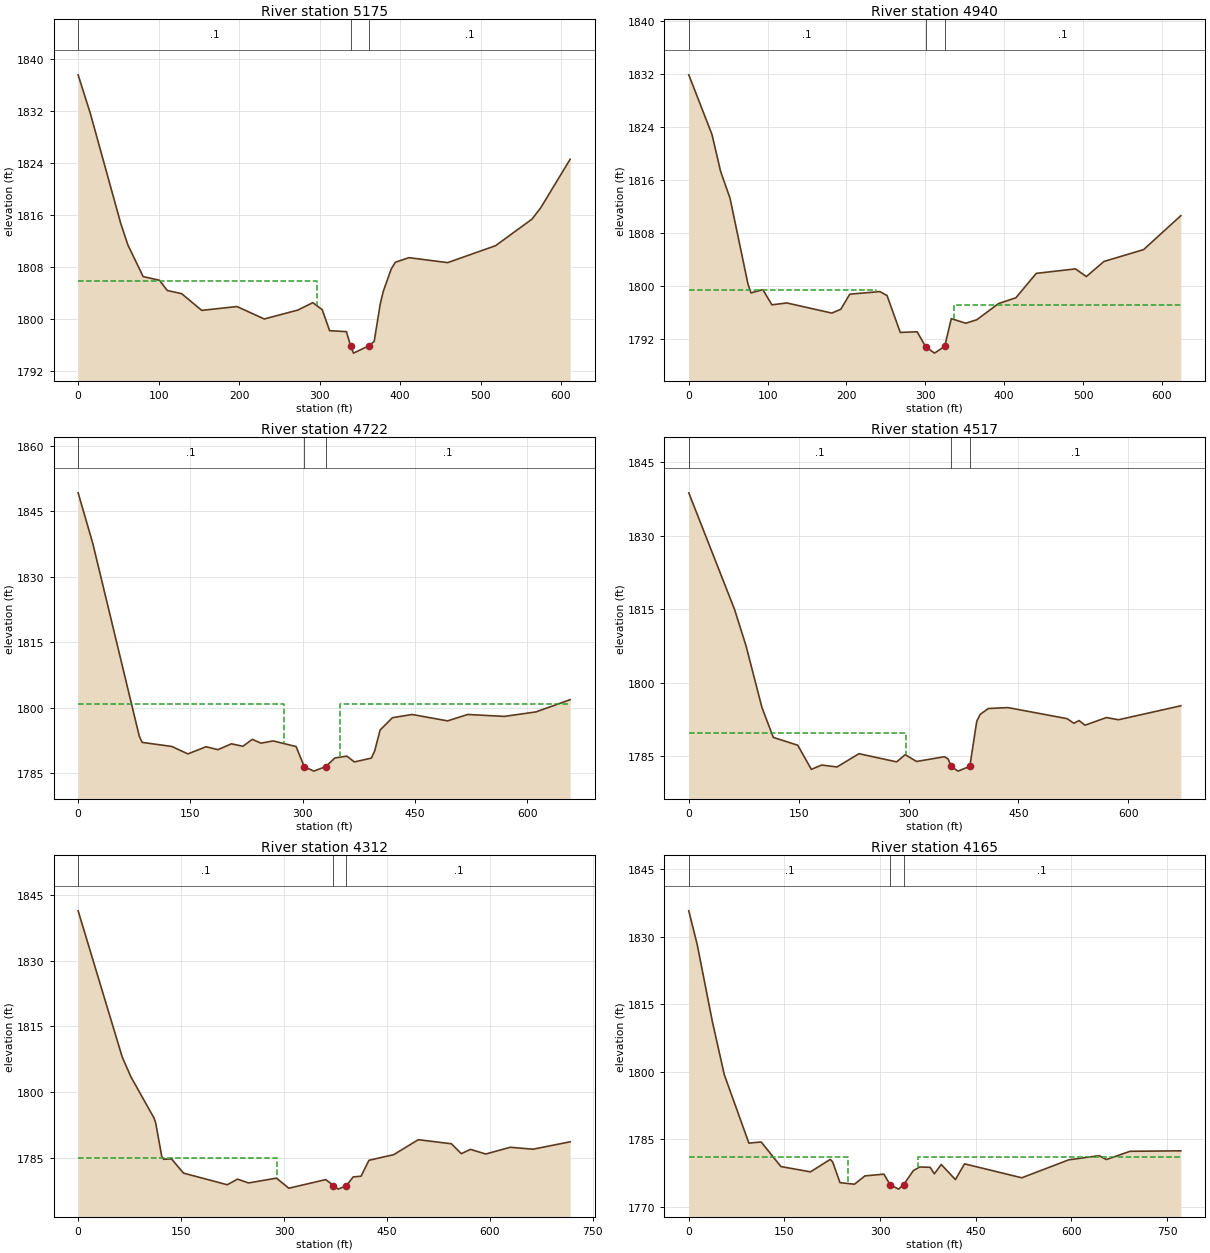
Type RM Length L Ch R = 1 ,5175    ,236,235.8,235.8
XS GIS Cut Line= 4
2042168.35492142254824.6901162432041977.95862539254650.077969111
2041847.73939702254497.1690267072041708.68992773254435.131571177
#Sta/Elev= 30
       0  1837.5    15.2 1831.55    52.9 1814.68    61.8 1811.36    80.8 1806.49
   101.1 1805.93   110.7 1804.36   128.6 1803.87   153.6  1801.3   197.3 1801.89
   231.3 1799.98   273.1 1801.35   291.6 1802.49   303.3 1801.41   312.5 1798.18
   333.4 1798.03   338.61795.834   342.1 1794.73   361.31795.856   367.9 1796.55
   375.3 1802.21     379 1804.16   389.1 1807.68   394.2  1808.7     411  1809.4
   459.2 1808.64   518.7 1811.24   563.9 1815.32   574.7 1817.04   611.4 1824.53
#Mann= 3 ,-1 , 0
       0      .1       0   338.6    .045       0   361.3      .1       0
#XS Ineff= 2 , 0
          296.36 1805.79
Permanent Ineff=
       T       F
Bank Sta=338.6,361.3
XS Rating Curve= 0 ,0
Exp/Cntr(USF)=0,0
Exp/Cntr=0.3,0.1

Type RM Length L Ch R = 1 ,4940    ,221.8,217.8,211.9
XS GIS Cut Line= 4
2042273.91141714254700.3899437082042152.57077253254492.236480177
2042009.52692318254324.5298981862041866.43293565254247.267028888
#Sta/Elev= 30
       0 1831.89    29.5 1822.85    40.3 1817.32    52.3 1813.25      75 1800.31
    78.8 1798.94      94 1799.43   105.4 1797.14   124.4 1797.42   181.4 1795.89
   192.8 1796.47   204.2 1798.75   242.3 1799.14   251.4 1798.55   268.2 1792.97
   289.7 1793.06   300.31790.819   311.6 1789.84   324.61790.865   332.9 1795.05
   351.2 1794.36   365.2 1794.88   392.9 1797.33   414.8  1798.2   440.7 1801.89
   490.4 1802.57   504.2 1801.41   526.5 1803.69   576.8 1805.48     624 1810.61
#Mann= 3 ,-1 , 0
       0      .1       0   300.3    .045       0   324.6      .1       0
#XS Ineff= 2 , 0
          237.18 1799.32  335.83         1797.08
Permanent Ineff=
       F       F
Bank Sta=300.3,324.6
XS Rating Curve= 0 ,0
Exp/Cntr(USF)=0,0
Exp/Cntr=0.3,0.1

Type RM Length L Ch R = 1 ,4722    ,203.1,204.8,205.2
XS GIS Cut Line= 4
2042476.26220317254508.9881930682042315.22707643254329.007757298
2042082.47042265254151.7337942482041969.29370346254102.664167745
#Sta/Elev= 30
       0 1849.27    19.5 1837.71    81.7 1793.44    85.5 1792.01   125.1 1791.07
   146.7 1789.36   170.9 1791.01   186.8 1790.33   204.8 1791.68   220.1 1791.11
   232.7  1792.7   244.3 1791.83   260.7 1792.34   291.2 1791.05   302.11786.446
   314.9 1785.41   330.91786.455   343.1 1788.44     359 1788.85   369.1 1787.52
   391.8  1788.4   396.2 1790.04   403.5 1794.85   419.9 1797.67   446.2 1798.41
   493.6 1796.94   520.5 1798.41   569.6 1797.97   611.7    1799   657.4 1801.81
#Mann= 3 ,-1 , 0
       0      .1       0   302.1    .045       0   330.9      .1       0
#XS Ineff= 2 , 0
             2751800.774     350        1800.774
Permanent Ineff=
       T       F
Bank Sta=302.1,330.9
XS Rating Curve= 0 ,0
Exp/Cntr(USF)=0,0
Exp/Cntr=0.3,0.1

Type RM Length L Ch R = 1 ,4517    ,202.2,204.7,206.8
XS GIS Cut Line= 4
2042623.76496632254396.6695752572042432.95863967254170.679103276
2042201.55522226253974.4598311972042141.83289231253933.413556319
#Sta/Elev= 30
       0 1838.74    62.6 1814.88    78.1 1807.52    99.8 1794.94   115.4  1788.8
   148.7 1787.21   167.3 1782.28   181.3 1783.16   202.3 1782.77   232.3 1785.48
   283.7 1783.81   295.4 1785.28   310.9 1783.89   348.9 1784.86     354  1784.4
   358.2 1782.89   358.2 1782.88   367.5 1781.92   383.61782.903   393.1 1792.12
   397.8 1793.51   408.9 1794.71   435.7 1794.89   516.5 1792.63   525.6 1791.69
   532.8 1792.24   540.8  1791.3   570.1 1792.86   586.5 1792.41   671.6 1795.26
#Mann= 3 ,-1 , 0
       0      .1       0   358.2    .045       0   383.6      .1       0
#XS Ineff= 2 , 0
             297 1789.76
Permanent Ineff=
       F       F
Bank Sta=358.2,383.6
XS Rating Curve= 0 ,0
Exp/Cntr(USF)=0,0
Exp/Cntr=0.3,0.1

Type RM Length L Ch R = 1 ,4312    ,131.7,147.1,156.6
XS GIS Cut Line= 4
2042771.26772946 254245.107103032042558.80962108254020.469867409
2042382.88889438253832.3700134842042255.77487804253752.224812565
#Sta/Elev= 30
       0 1841.41    64.1 1808.08    76.7 1803.55   110.6 1794.07   112.9 1793.05
   121.9 1785.28   124.5 1784.66   136.1 1784.75   153.5  1781.5   217.3 1778.84
   232.3 1780.12   248.3 1779.25     289 1780.35     307 1778.05   360.9 1780.02
   372.11778.663   378.9 1777.84     3911778.613   400.7 1780.62   412.3 1780.79
   423.8 1784.43   459.8 1785.71   495.7 1789.13     544  1788.2   558.4 1785.94
   571.7 1786.92     594 1785.86   629.7  1787.4     663 1786.96     717 1788.65
#Mann= 3 ,-1 , 0
       0      .1       0   372.1    .045       0     391      .1       0
#XS Ineff= 2 , 0
          289.06 1785.05
Permanent Ineff=
       F       F
Bank Sta=372.1,391
XS Rating Curve= 0 ,0
Exp/Cntr(USF)=0,0
Exp/Cntr=0.3,0.1

Type RM Length L Ch R = 1 ,4165    ,145.3,137.9,136.5
XS GIS Cut Line= 4
2042779.38714762254223.455321283 2042644.0635117254005.584267458
2042623.76496632253798.5391045052042397.84752542253590.877618422
#Sta/Elev= 30
       0 1835.78    13.1 1828.36      37 1811.15    55.6  1799.4    94.2 1784.16
   113.5 1784.41   144.4 1778.95   190.8 1777.77   221.7 1780.53   225.5    1780
   237.1 1775.37   259.7 1775.02   276.2 1776.87   305.9 1777.26   315.6 1774.92
   328.9 1773.93   336.81774.921   352.1 1778.04   361.9 1778.85   378.4 1778.78
     385 1777.33   395.8 1779.41     418 1776.05   432.3 1779.55   522.1 1776.45
   595.9 1780.45   643.3 1781.36   654.7 1780.51   691.8 1782.34   771.4 1782.44
#Mann= 3 ,-1 , 0
       0      .1       0   315.6    .045       0   336.8      .1       0
#XS Ineff= 2 , 0
             2501781.177     360        1781.177
Permanent Ineff=
       F       F
Bank Sta=315.6,336.8
XS Rating Curve= 0 ,0
Exp/Cntr(USF)=0,0
Exp/Cntr=0.3,0.1

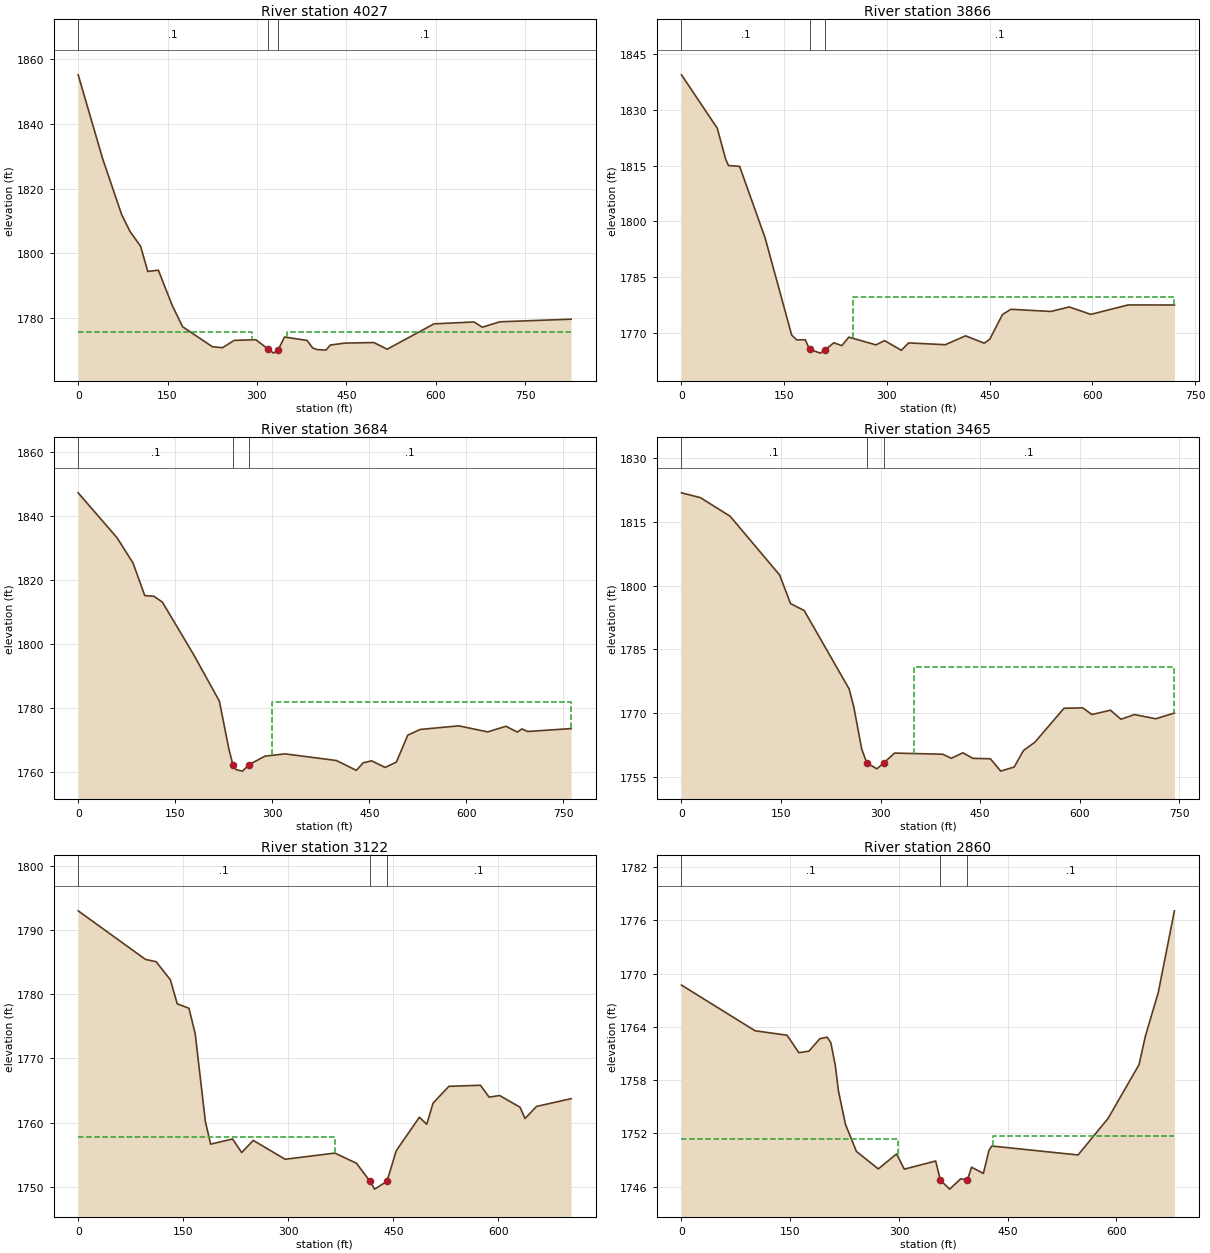
Type RM Length L Ch R = 1 ,4027    ,165.7,161,155.4
XS GIS Cut Line= 4
2042888.99929271254188.2711759452042811.86482024253993.405140225
 2042650.8296935253669.9816503842042471.09668657253487.185012657
#Sta/Elev= 30
       0 1855.12    41.2 1829.13    72.9    1812      87 1806.73   104.7 1802.21
   116.8 1794.41   134.5 1794.81   157.6 1784.01   175.2 1777.34   225.2 1771.17
   242.1 1770.87   261.9 1773.13   298.1 1773.33     3191770.417   327.9 1769.19
   335.81770.309   346.2 1774.16     384 1773.12   393.7 1770.76   401.1 1770.28
   415.8 1770.13   423.1 1771.69   447.6 1772.29   496.1 1772.46   518.6  1770.4
   597.1 1778.23   664.2 1778.81   678.2  1777.2   707.5 1778.86   827.2 1779.67
#Mann= 3 ,-1 , 0
       0      .1       0     319    .045       0   335.8      .1       0
#XS Ineff= 2 , 0
             291 1775.76     350         1775.76
Permanent Ineff=
       F       F
Bank Sta=319,335.8
XS Rating Curve= 0 ,0
Exp/Cntr(USF)=0,0
Exp/Cntr=0.3,0.1

Type RM Length L Ch R = 1 ,3866    ,183.5,182.1,178.9
XS GIS Cut Line= 4
2043010.79056504253948.7483403732042929.59638349253841.842667999
2042718.49151146253605.0263051442042522.48942206253421.841791075
#Sta/Elev= 30
       0 1839.41    52.2 1825.08    64.5 1816.75    68.6 1815.03    84.9 1814.81
   122.2 1795.54   160.9 1769.48   168.3 1768.18   180.7 1768.22   187.11765.621
   202.8 1764.62   209.3 1765.44   222.5 1767.41   234.1 1766.63   244.4 1768.91
     284 1766.84   296.5 1767.98   321.1 1765.38   331.7 1767.37   385.2 1766.88
   414.8 1769.27   442.2 1767.29   450.2 1768.36   468.8 1775.02     481  1776.4
   539.3 1775.82   566.3 1777.03   597.7 1775.03   652.2 1777.57   719.8 1777.56
#Mann= 3 ,-1 , 0
       0      .1       0   187.1    .045       0   209.3      .1       0
#XS Ineff= 2 , 0
                             250         1779.59
Permanent Ineff=
       F       F
Bank Sta=187.1,209.3
XS Rating Curve= 0 ,0
Exp/Cntr(USF)=0,0
Exp/Cntr=0.3,0.1

Type RM Length L Ch R = 1 ,3684    ,224.7,219,216.4
XS GIS Cut Line= 4
2043188.06452809253840.4894316392043066.27325576253713.285213878
 2042717.1382751253399.3343785512042630.68293409253321.292476767
#Sta/Elev= 30
       0 1847.33    60.2 1833.27    84.8 1825.41   102.9 1815.25   117.1 1815.02
   130.2 1813.19   178.6 1796.77   218.3 1782.27   232.9 1767.38   239.4  1762.2
   244.5 1760.84   254.1 1760.41   263.9  1762.4   288.7 1765.08   319.8  1765.8
   399.2 1763.73   430.1 1760.65   440.5    1763   453.6 1763.63   474.5 1761.57
   491.9 1763.23   509.5 1771.64   528.8 1773.43   588.4 1774.55   633.1 1772.66
   661.3 1774.42     679 1772.61   686.1  1773.6   694.9 1772.79   762.1  1773.7
#Mann= 3 ,-1 , 0
       0      .1       0   239.4    .045       0   263.9      .1       0
#XS Ineff= 2 , 0
                             300        1781.971
Permanent Ineff=
       F       F
Bank Sta=239.4,263.9
XS Rating Curve= 0 ,0
Exp/Cntr(USF)=0,0
Exp/Cntr=0.3,0.1

Type RM Length L Ch R = 1 ,3465    ,337.8,343.7,339.8
XS GIS Cut Line= 4
  2043323.388164253626.6780868912043144.76096459253491.354450974
2042871.40722004253330.3193242342042706.95875664253213.990723703
#Sta/Elev= 30
       0 1821.78    28.5 1820.65    73.3 1816.28   147.9 1802.48   164.4 1795.75
   184.9 1794.13   252.6 1775.72   259.4 1771.68   271.6  1761.6   279.3  1758.3
   294.5 1756.95     3051758.351   321.1 1760.64   393.6 1760.37   406.7 1759.42
     424 1760.71     439 1759.41   465.5  1759.3   481.1  1756.4   501.4 1757.37
   515.3 1761.24   532.6  1763.2   576.4 1771.17   604.8 1771.26   618.4  1769.7
   646.5 1770.71   662.2 1768.59   682.7 1769.69   714.8  1768.7   742.8 1770.05
#Mann= 3 ,-1 , 0
       0      .1       0   279.3    .045       0     305      .1       0
#XS Ineff= 2 , 0
                             350        1780.978
Permanent Ineff=
       F       F
Bank Sta=279.3,305
XS Rating Curve= 0 ,0
Exp/Cntr(USF)=0,0
Exp/Cntr=0.3,0.1

Type RM Length L Ch R = 1 ,3122    ,254.8,261.2,266.8
XS GIS Cut Line= 4
2043342.22311204253409.3927784972043065.34276095253157.683368414
2042935.61560345   253070.5531882042794.27190938252969.899345251
#Sta/Elev= 30
       0 1792.96    96.1  1785.4   111.3 1785.04   131.6 1782.24   141.5 1778.48
   158.2  1777.8   167.1 1773.84   181.7 1760.13   189.2 1756.64   220.5 1757.45
   233.5 1755.33     250 1757.23   295.6 1754.29   366.6 1755.25   397.4 1753.67
   416.71750.866   423.4 1749.64     4411750.856   454.3 1755.63   487.3 1760.83
   497.8 1759.74   506.8 1763.02   529.4 1765.64   574.5 1765.81   586.9 1763.96
   601.9 1764.21     631 1762.39   638.2 1760.63   654.5 1762.51     704 1763.72
#Mann= 3 ,-1 , 0
       0      .1       0   416.7    .045       0     441      .1       0
#XS Ineff= 2 , 0
          367.02 1757.69
Permanent Ineff=
       F       F
Bank Sta=416.7,441
XS Rating Curve= 0 ,0
Exp/Cntr(USF)=0,0
Exp/Cntr=0.3,0.1

Type RM Length L Ch R = 1 ,2860    ,334.2,340.4,345.4
XS GIS Cut Line= 4
2043381.46298428253221.1566754222043295.75368249   253070.553188
2043082.76879703 252822.716230382042949.53723466252701.975126976
#Sta/Elev= 30
       0 1768.71   101.5 1763.56   145.6 1763.06   161.9 1761.09   175.8 1761.26
   190.7 1762.66     201 1762.84   206.1 1762.19   212.2 1759.64   216.5 1756.78
   226.2 1753.01   241.3 1749.96   271.5 1747.99   296.7 1749.68   307.3 1747.96
   350.6 1748.88   357.1 1746.72   369.9 1745.71   385.2 1746.88   394.31746.722
   400.1 1748.18   416.4 1747.48   424.1 1750.07     428 1750.57     547 1749.56
   588.4 1753.68   631.1 1759.74   639.9 1762.97   657.7  1767.9   679.9 1777.08
#Mann= 3 ,-1 , 0
       0      .1       0   357.1    .045       0   394.3      .1       0
#XS Ineff= 2 , 0
           299.1 1751.35  429.24          1751.7
Permanent Ineff=
       F       F
Bank Sta=357.1,394.3
XS Rating Curve= 0 ,0
Exp/Cntr(USF)=0,0
Exp/Cntr=0.3,0.1

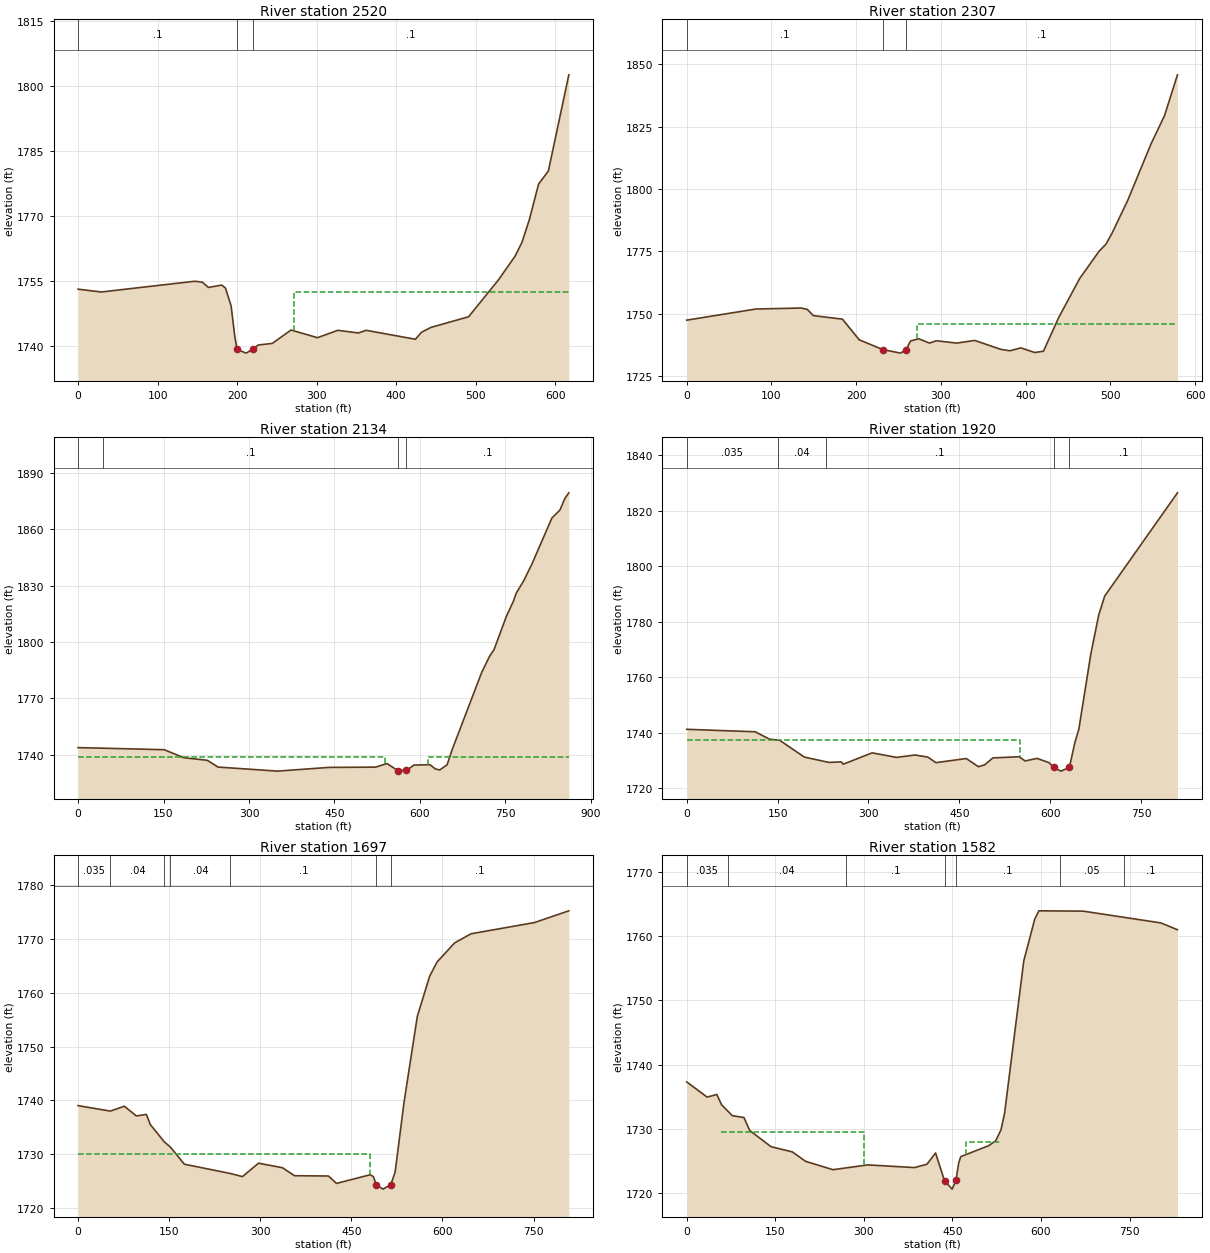
Type RM Length L Ch R = 1 ,2520    ,213.3,213.1,216.3
XS GIS Cut Line= 4
 2043559.1216786252975.2069597862043500.99366302252859.504528777
2043369.33027928252673.6268105622043208.41056354252469.713277637
#Sta/Elev= 30
       0 1753.14    29.1 1752.49   146.9 1754.97   156.2 1754.75   163.9 1753.54
   180.6 1754.08   185.3  1753.4   192.4 1749.29   197.1  1742.2   199.81739.284
   211.2 1738.39   219.91739.282   226.4 1740.26   244.2 1740.63   267.7 1743.72
     301 1741.95   326.5 1743.65   352.4 1743.04   362.2 1743.65   424.1 1741.59
   431.9 1743.22   443.6 1744.32     491 1746.78   528.6  1755.3   549.5 1760.77
   558.2 1763.99   567.4  1769.2     579 1777.38   591.3  1780.4     617 1802.57
#Mann= 3 ,-1 , 0
       0      .1       0   199.8    .045       0   219.9      .1       0
#XS Ineff= 2 , 0
                        270.9933         1752.58
Permanent Ineff=
       F       T
Bank Sta=199.8,219.9
XS Rating Curve= 0 ,0
Exp/Cntr(USF)=0,0
Exp/Cntr=0.3,0.1

Type RM Length L Ch R = 1 ,2307    ,175.1,172.9,170.8
XS GIS Cut Line= 4
2043711.58046883 252860.18834881 2043648.1468566 252712.35133519
2043489.37630563252476.1317349582043422.06519006252360.559819548
#Sta/Elev= 30
       0 1747.35    81.6 1751.82   135.2 1752.22   142.3 1751.66   149.5 1749.17
   183.8 1747.75   203.6 1739.46   231.21735.565   252.4 1734.11   258.9 1735.56
   264.2 1738.98   273.7 1739.88   286.6 1738.14   294.5 1739.08   318.6 1738.14
   339.9 1739.21   370.6 1735.63   381.5 1735.05   394.3 1736.22   410.8 1734.35
     421 1734.88   439.2  1748.5   463.7 1764.02   486.5 1774.94   494.6 1777.79
   501.5 1781.93   520.6 1795.52     548 1818.13   563.9 1829.44   579.2 1845.85
#Mann= 3 ,-1 , 0
       0      .1       0   231.2    .045       0   258.9      .1       0
#XS Ineff= 2 , 0
                        272.2349         1745.71
Permanent Ineff=
       F       T
Bank Sta=231.2,258.9
XS Rating Curve= 0 ,0
Exp/Cntr(USF)=0,0
Exp/Cntr=0.3,0.1

Type RM Length L Ch R = 1 ,2134    ,198.6,213.7,225.9
XS GIS Cut Line= 4
2043977.08203766253050.5549593452043858.22740271252677.499263025
2043581.34705162252356.085708611 2043553.1487579252320.266254429
#Sta/Elev= 30
       0 1743.85    44.4 1743.55   151.1 1742.75   185.5  1738.5   226.9  1737.1
   245.6 1733.51   350.1 1731.35   440.7 1733.34   522.2 1733.47   542.1 1735.38
   561.21731.664   576.41731.708   589.6 1734.59   617.5 1734.75   627.5 1732.45
   634.8 1731.99   647.7 1734.74     657 1743.15   708.4 1783.88   722.2 1792.46
   730.1 1796.04   751.7  1813.7   764.1 1821.82   769.1 1826.09     782 1832.57
   796.6 1841.58   831.6 1866.02   845.9 1870.35   854.2 1876.38   861.3 1879.43
#Mann= 4 ,-1 , 0
       0    .035       0    44.4      .1       0   561.2    .045       0
   576.4      .1       0
#XS Ineff= 2 , 0
           538.51738.836     615        1738.836
Permanent Ineff=
       F       T
Bank Sta=561.2,576.4
XS Rating Curve= 0 ,0
Exp/Cntr(USF)=0,0
Exp/Cntr=0.3,0.1

Type RM Length L Ch R = 1 ,1920    ,211.3,222.8,232.1
XS GIS Cut Line= 4
2044044.98017473253058.7598748352043916.31418965 252547.77210552
2043908.56928473252375.4479709252043878.15583303252269.000889972
#Sta/Elev= 30
       0 1741.22     113 1740.33   136.7 1737.67   153.6 1737.25   194.2 1731.22
   234.8 1729.29   255.1  1729.5   258.4 1728.66   306.1 1732.74   346.4  1731.1
   376.9 1731.97     398 1731.21   411.5 1729.21   461.4  1730.7   481.6 1727.75
   491.9 1728.43   505.4 1730.92   548.7 1731.34   558.6 1729.83   578.2 1730.74
     598 1729.23   605.9  1727.5   617.7 1726.16   631.71727.495   640.7  1736.4
   647.3 1741.25     667 1768.23   680.1 1782.35     690 1789.21   810.1 1826.37
#Mann= 5 ,-1 , 0
       0    .035       0     150     .04       0     230      .1       0
   605.9    .045       0   631.7      .1       0
#XS Ineff= 2 , 0
             5501737.306
Permanent Ineff=
       F       F
Bank Sta=605.9,631.7
XS Rating Curve= 0 ,0
Exp/Cntr(USF)=0,0
Exp/Cntr=0.3,0.1

Type RM Length L Ch R = 1 ,1697    ,109,115.8,126.2
XS GIS Cut Line= 4
2044099.49994409253070.9969879142044059.59493078252644.583417091
2044138.98020627252470.323056264 2044183.6885243252287.497970036
#Sta/Elev= 30
       0 1739.04    53.1 1738.03    76.2 1738.93      96 1737.13   112.4 1737.41
     119 1735.52   142.1 1732.31     152 1731.36     175 1728.18   250.8 1726.46
   270.6 1725.88   297.1 1728.37   336.5 1727.53   356.3 1726.05   412.3 1725.99
   425.5 1724.62   481.1 1726.23   486.5 1725.84   490.71724.383   502.1 1723.56
   514.9 1724.39     522 1726.71   536.8 1739.75   558.6 1755.62   578.9 1763.04
     591 1765.66   619.9 1769.21   646.9  1770.9   751.6 1772.99     808 1775.16
#Mann= 7 ,-1 , 0
       0    .035       0    53.1     .04       0   142.1    .035       0
     152     .04       0   250.8      .1       0   490.7    .045       0
   514.9      .1       0
#XS Ineff= 2 , 0
             481    1730
Permanent Ineff=
       F       F
Bank Sta=490.7,514.9
XS Rating Curve= 0 ,0
Exp/Cntr(USF)=0,0
Exp/Cntr=0.3,0.1

Type RM Length L Ch R = 1 ,1582    ,72.1,71.5,70.2
XS GIS Cut Line= 5
2044141.44679961253085.4722121262044144.78888496252683.307941719
2044226.11038668252609.731344925 2044301.6232097252530.346069438
2044404.00408674252347.256179841
#Sta/Elev= 30
       0 1737.29    34.6 1734.93      51 1735.34    58.9 1733.76    77.2 1732.04
    96.9 1731.76   106.7 1729.74   142.8 1727.22   178.9 1726.41   201.2 1724.95
   247.8 1723.64   306.7 1724.39   385.6 1723.97   406.8 1724.49   421.5 1726.24
   436.71721.911   449.5 1720.62     4561721.969   460.6 1724.65   464.1 1725.67
   511.5 1727.38   523.3 1728.14   532.3 1729.84   538.4 1732.43   570.9 1756.12
   589.5 1762.62   596.4  1763.9   671.5 1763.85   803.1 1762.02   831.2 1760.96
#Mann= 7 ,-1 , 0
       0    .035       0      70     .04       0     270      .1       0
   436.7    .045       0     456      .1       0  631.41     .05       0
  741.41      .1       0
#XS Ineff= 2 ,-1
57.90636300.85641729.569473.3764530.6863 1727.88
Permanent Ineff=
       T       T
Bank Sta=436.7,456
XS Rating Curve= 0 ,0
Exp/Cntr(USF)=0,0
Exp/Cntr=0.3,0.1

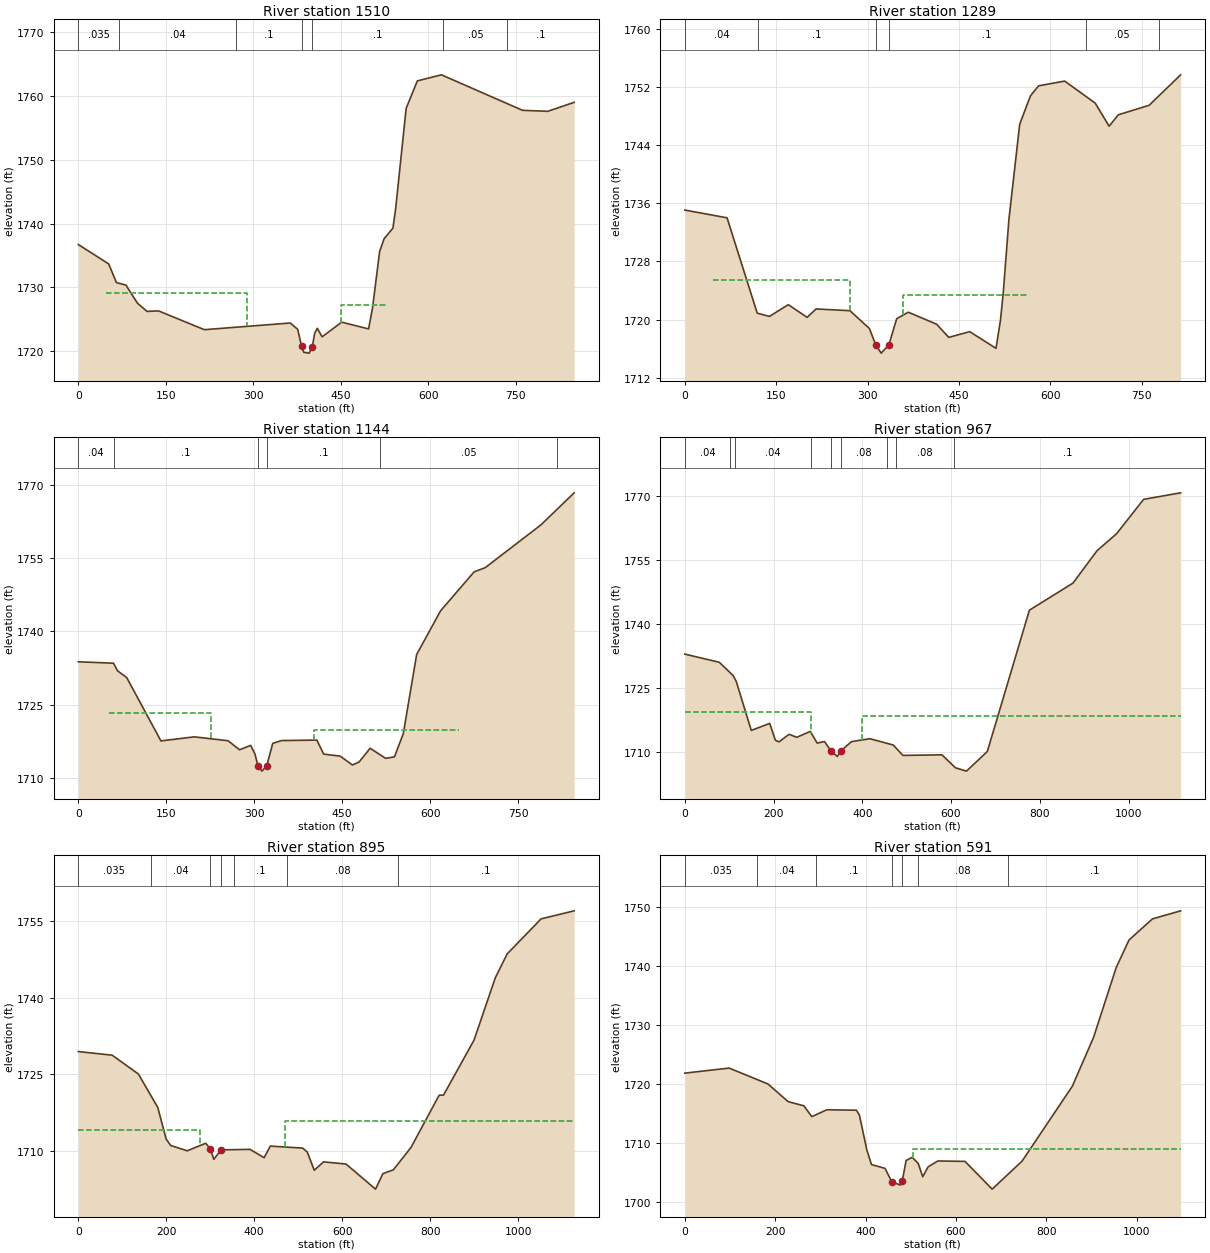
Type RM Length L Ch R = 1 ,1510    ,226.1,220.8,212.7
XS GIS Cut Line= 4
2044173.57999695253089.8196835522044189.32208828252741.394728661
2044286.13339985252644.5834170912044467.84489946252328.804286664
#Sta/Elev= 30
       0  1736.7    52.1 1733.65    65.3 1730.72    81.6 1730.33   101.3  1727.5
   117.8  1726.2   137.5 1726.28   216.1 1723.33   363.3 1724.38   376.1 1723.38
   382.71720.727   386.5 1719.77   395.8 1719.65   401.21720.683   405.1 1722.75
   409.7 1723.55   417.9 1722.21   451.5 1724.51   497.6 1723.45   504.4 1726.76
   516.5 1735.59   524.1  1737.6   539.3 1739.27   543.9 1742.25     562 1758.08
   581.2 1762.39   622.5 1763.34   761.4 1757.77   804.7 1757.61     850 1759.02
#Mann= 7 ,-1 , 0
       0    .035       0      70     .04       0     270      .1       0
   382.7    .045       0   401.2      .1       0  625.69     .05       0
  735.69      .1       0
#XS Ineff= 2 ,-1
48.17752288.62751729.113450.2875528.2175 1727.16
Permanent Ineff=
       T       T
Bank Sta=382.7,401.2
XS Rating Curve= 0 ,0
Exp/Cntr(USF)=0,0
Exp/Cntr=0.3,0.1

Type RM Length L Ch R = 1 ,1289    ,144.3,145.3,146.9
XS GIS Cut Line= 4
2044293.95954919  253134.03495252044367.45490157252904.037732099
2044470.07489184252691.0528466442044596.70936729252379.694686829
#Sta/Elev= 30
       0 1735.09    69.4 1734.02   118.9 1720.88   138.9 1720.43   169.9 1722.05
   200.9  1720.3   215.5 1721.46   271.1 1721.22   303.1 1718.76   313.41716.518
   322.4 1715.37     335  1716.5   347.9 1720.12     367 1721.01   413.5 1719.35
   433.3 1717.54   467.7 1718.33   510.9 1716.03   518.2 1719.87   522.9 1723.76
   532.1  1733.8   549.8 1746.91   567.5 1750.84   580.8 1752.21   623.6 1752.87
   673.8 1749.83   696.6 1746.65   711.7 1748.22   762.3 1749.53     814 1753.73
#Mann= 6 ,-1 , 0
       0     .04       0     120      .1       0   313.4    .045       0
     335      .1       0  657.87     .05       0  777.87      .1       0
#XS Ineff= 2 ,-1
46.04183271.13181725.501357.7819561.7418 1723.33
Permanent Ineff=
       T       T
Bank Sta=313.4,335
XS Rating Curve= 0 ,0
Exp/Cntr(USF)=0,0
Exp/Cntr=0.3,0.1

Type RM Length L Ch R = 1 ,1144    ,160.3,177,184.7
XS GIS Cut Line= 4
2044366.68382871 253166.454582542044481.69224922252985.359233818
2044735.33788554252540.0272005952044796.08011886252437.955200278
#Sta/Elev= 30
       0 1733.78    60.1 1733.49    66.9 1731.93    82.5 1730.56   140.9  1717.6
     198 1718.43   255.5 1717.63     275 1715.79     294 1716.69   301.2 1714.95
   306.61712.471   313.2 1711.42   321.41712.518   331.6 1717.09   346.7 1717.67
   406.9 1717.77   418.5  1714.9   446.6 1714.49   467.6 1712.68   478.9 1713.28
   497.8  1716.1   524.2 1714.03   539.3 1714.34   554.4 1719.11   577.1 1735.26
     618 1744.21   675.2 1752.17   694.1 1753.03     789 1761.76   845.8 1768.33
#Mann= 6 ,-1 , 0
       0     .04       0      60      .1       0   306.6    .045       0
   321.4      .1       0  514.53     .05       0  817.03      .1       0
#XS Ineff= 2 ,-1
51.47099 226.2911723.279 402.481 649.181 1719.88
Permanent Ineff=
       T       T
Bank Sta=306.6,321.4
XS Rating Curve= 0 ,0
Exp/Cntr(USF)=0,0
Exp/Cntr=0.3,0.1

Type RM Length L Ch R = 1 ,967     ,83.4,71.8,78
XS GIS Cut Line= 6
2044400.81302748253185.072749135 2044426.2934479253151.653609006
2044569.18276542  253040.05150642044666.83901545253006.414353624
2044912.23848608252788.1274293812045026.82181942252340.210762709
#Sta/Elev= 30
       0 1732.95    77.8 1731.03   108.9 1727.91   115.9 1726.55   149.8 1715.03
   191.5 1716.68     204 1712.74   212.3 1712.34     235 1714.12   252.3 1713.41
   282.8 1714.79   298.3 1712.06   314.8 1712.42     3291710.274   343.6 1708.92
   352.2 1710.27   375.5 1712.39     417 1713.08   469.7 1711.61   491.6 1709.16
   579.5  1709.3   610.1 1706.25   634.8 1705.47   681.8 1710.08   776.6 1743.26
   874.8 1749.62     929 1757.23   973.1 1761.22    1034 1769.29  1117.4 1770.82
#Mann= 9 ,-1 , 0
       0     .04       0  102.02      .1       0  112.02     .04       0
  283.33      .1       0     329    .045       0   352.2     .08       0
  456.62      .1       0  476.62     .08       0  606.62      .1       0
#XS Ineff= 2 ,-1
       0285.0802 1719.37399.96021117.395 1718.41
Permanent Ineff=
       T       T
Bank Sta=329,352.2
XS Rating Curve= 0 ,0
Exp/Cntr(USF)=0,0
Exp/Cntr=0.3,0.1

Type RM Length L Ch R = 1 ,895     ,324,304.1,272.3
XS GIS Cut Line= 4
2044501.97472018253218.953862405 2044551.4520211253178.080404727
2044967.79404166  252846.11354052045084.11348608252328.057984933
#Sta/Elev= 30
       0 1729.43      77 1728.72   136.6 1725.03   180.6  1718.5   199.7 1712.29
   210.1 1711.02   247.8 1709.99   289.7 1711.47   299.7 1710.41   308.2 1708.31
   324.5 1710.17   390.4 1710.27   422.6 1708.64   436.6 1710.91   510.2 1710.52
   520.8 1709.72   536.5 1706.18   557.6 1707.82   608.7  1707.4   675.9 1702.48
   692.7 1705.52   716.3 1706.25   756.6 1710.65   820.5 1720.87   830.6 1720.91
   899.9 1731.67   948.3 1743.89   975.2 1748.55  1052.5 1755.43  1127.6    1757
#Mann= 7 ,-1 , 0
       0    .035       0  164.18     .04       0   299.7    .045       0
   324.5     .08       0  354.18      .1       0  474.18     .08       0
  726.66      .1       0
#XS Ineff= 2 , 0
        277.4327 1714.05468.8927         1715.83
Permanent Ineff=
       T       T
Bank Sta=299.7,324.5
XS Rating Curve= 0 ,0
Exp/Cntr(USF)=0,0
Exp/Cntr=0.3,0.1

Type RM Length L Ch R = 1 ,591     ,195.3,180.2,154.5
XS GIS Cut Line= 4
2044804.59959722253335.0024293812045051.12737498253052.016318277
2045007.72459725252815.9052071572045103.21070835252343.682984933
#Sta/Elev= 30
       0 1721.84    98.1  1722.7   184.1    1720   228.8 1717.01   263.6  1716.3
     281 1714.47   314.4 1715.64   379.8 1715.56   386.4 1714.72     403 1708.78
   413.1 1706.35   443.1 1705.71   457.71703.482   476.5 1702.88   481.41703.644
   489.8 1707.05   503.2 1707.58   516.5 1706.55   526.5 1704.29   538.4 1705.96
   559.9 1706.96     620 1706.89   680.2 1702.19   746.4 1706.94   857.6 1719.63
   904.5 1727.89   954.7 1739.74     983  1744.4    1035 1747.98  1097.2 1749.34
#Mann= 7 ,-1 , 0
       0    .035       0     160     .04       0     290      .1       0
   457.7    .045       0   481.4      .1       0  515.31     .08       0
  715.38      .1       0
#XS Ineff= 1 ,-1
  504.471097.156 1709.03
Permanent Ineff=
       T
Bank Sta=457.7,481.4
XS Rating Curve= 0 ,0
Exp/Cntr(USF)=0,0
Exp/Cntr=0.3,0.1

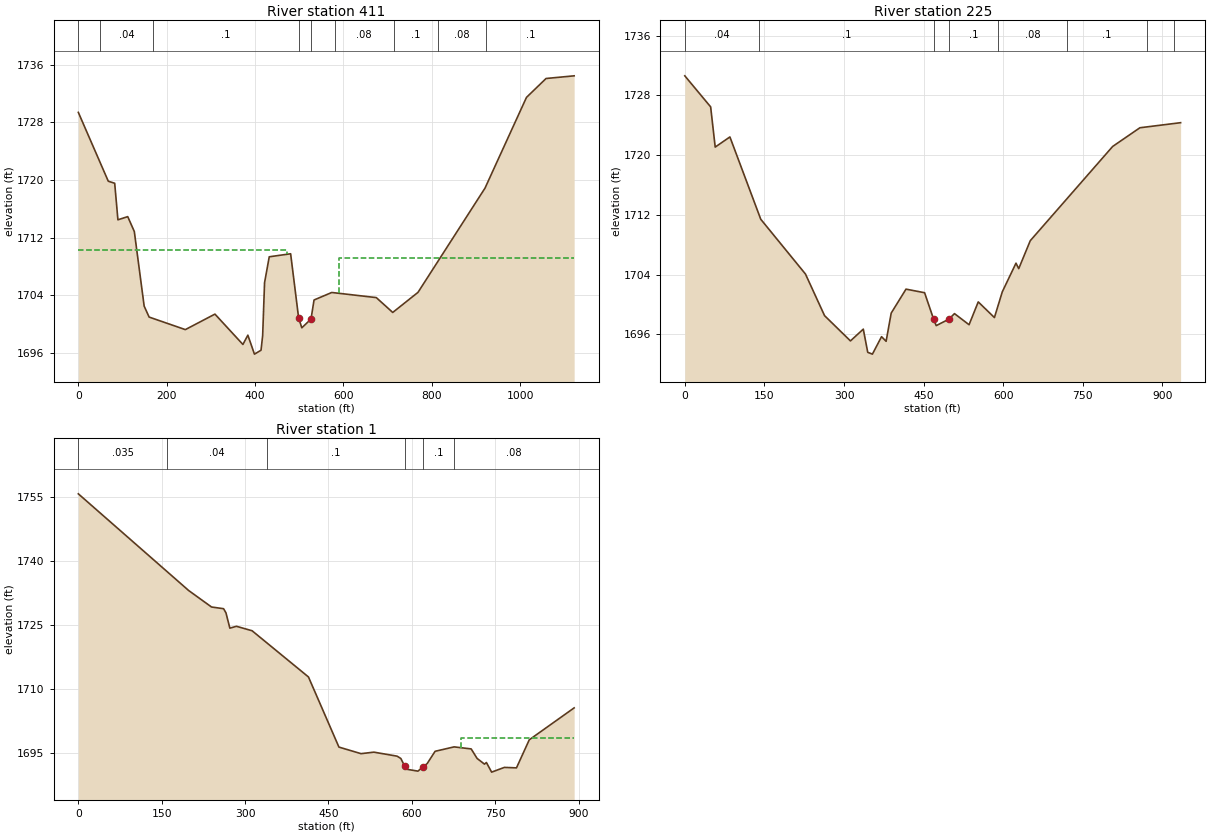
Type RM Length L Ch R = 1 ,411     ,180.4,185.5,188.6
XS GIS Cut Line= 3
2045607.11695832253096.7211793812045040.15999791252792.143711343
2045150.08570832252326.321873829
#Sta/Elev= 30
       0 1729.39    67.8 1719.84    82.3 1719.56    89.6 1714.49   111.8 1714.93
   126.7 1712.87     149 1702.52   160.2    1701   242.2 1699.26   309.2 1701.41
   372.5  1697.2   383.7 1698.49   398.6 1695.86   413.5  1696.4   417.2 1698.44
   421.5 1705.77   432.1 1709.36   480.5 1709.78   498.61700.882   505.8 1699.51
   526.6 1700.72   533.5 1703.37   573.6 1704.41   674.4  1703.7   711.6 1701.64
   768.8 1704.43   920.4 1718.88  1014.3 1731.47  1058.6 1734.09  1122.2 1734.46
#Mann= 9 ,-1 , 0
       0    .035       0      50     .04       0     170      .1       0
   498.6    .045       0   526.6      .1       0     580     .08       0
  713.59      .1       0  813.59     .08       0  923.59      .1       0
#XS Ineff= 2 , 0
          473.26 1710.24  590.63         1709.15
Permanent Ineff=
       F       F
Bank Sta=498.6,526.6
XS Rating Curve= 0 ,0
Exp/Cntr(USF)=0,0
Exp/Cntr=0.3,0.1

Type RM Length L Ch R = 1 ,225     ,210.5,223.9,239.4
XS GIS Cut Line= 3
2045611.45221618 253007.298974322045114.09299999252587.467999995
2045186.47859746252313.488731518
#Sta/Elev= 30
       0 1730.63    48.7 1726.47    57.3 1721.08      85 1722.44   143.1 1711.41
   227.4 1704.06   263.3 1698.49   312.1  1695.1   336.3 1696.68   344.7 1693.57
   353.5 1693.33   370.7 1695.67   379.3 1695.05   388.9 1698.83   416.8 1702.04
   451.8 1701.56  468.84 1698.01   473.7 1697.15  497.73 1698.02   508.1 1698.76
   535.6 1697.27   552.9 1700.33   583.4 1698.23   598.2 1701.68     624 1705.52
   629.2 1704.79   650.9 1708.53   806.1 1721.16   857.5 1723.67   934.2 1724.35
#Mann= 8 ,-1 , 0
       0     .04       0     140      .1       0  468.84    .045       0
  497.73      .1       0     590     .08       0  720.86      .1       0
  870.86     .08       0  920.86      .1       0
Bank Sta=468.84,497.73
XS Rating Curve= 0 ,0
Exp/Cntr(USF)=0,0
Exp/Cntr=0.3,0.1

Type RM Length L Ch R = 1 ,1       ,259,230.7,214.3
XS GIS Cut Line= 4
2045753.79288326253103.4690339342045463.35894855252689.116620413
2045399.46348291252470.323056264 2045306.5246238252342.532124991
#Sta/Elev= 30
       0 1755.83   198.5 1733.12   239.6 1729.25   261.3 1728.85   265.6 1727.87
   272.6 1724.28   284.4 1724.72   312.6 1723.67     414 1712.82   468.8 1696.35
   508.5 1694.81   531.7 1695.16   573.4 1694.22   580.2 1693.67   587.1 1691.86
   590.5 1691.15     611  1690.7   619.5 1691.66   627.5 1692.47   641.8 1695.36
     676  1696.4   706.7 1695.92   717.4 1693.68   730.6 1692.35   734.1 1692.73
   743.5 1690.47   766.5 1691.58   788.2 1691.47   811.2 1698.06891.9495 1705.56
#Mann= 6 ,-1 , 0
       0    .035       0     160     .04       0     340      .1       0
   587.1    .045       0   619.5      .1       0     676     .08       0
#XS Ineff= 2 , 0
                          688.87         1698.47
Permanent Ineff=
       F       T
Bank Sta=587.1,619.5
XS Rating Curve= 0 ,0
Exp/Cntr(USF)=0,0
Exp/Cntr=0.3,0.1
LCMann Table=0

Chan Stop Cuts=-1
Use User Specified Reach Order=0
Composite Channel Slope=5